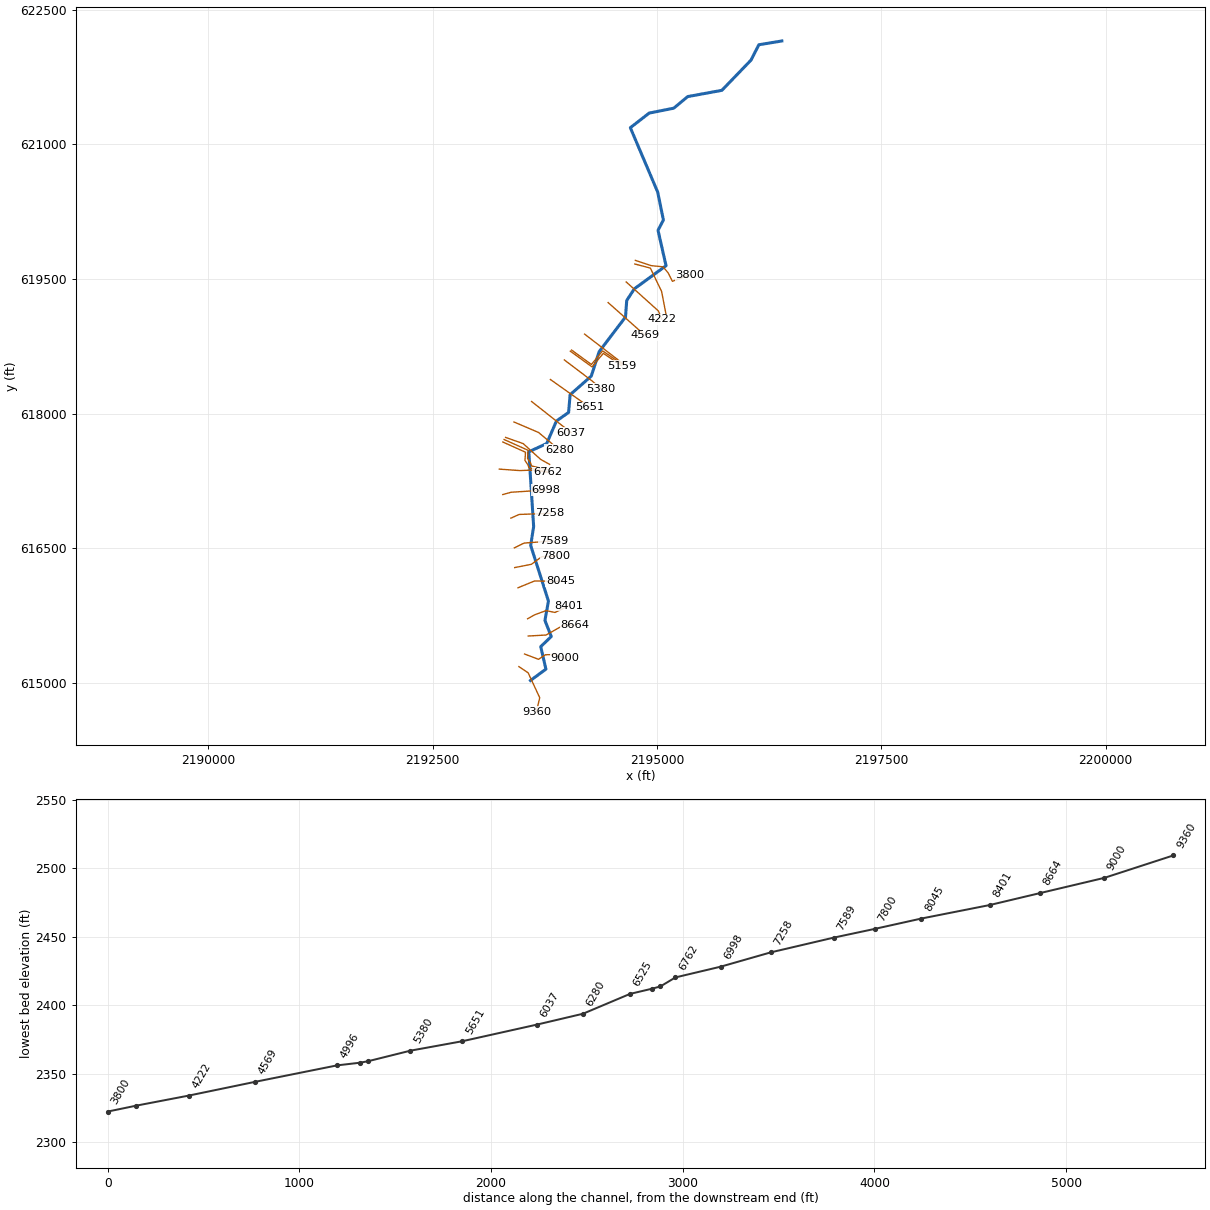
--- UPTROUTRN.prj (project) ---

Proj Title=UPTROUTRN
Current Plan=p01
Default Exp/Contr=0,0
English Units
Geom File=g01
Flow File=f01
Plan File=p01
BEGIN DESCRIPTION:
----------MODEL BY WOOD PLC 2022----------
AFH study
Randolph County, WV
HEC-RAS Version: RAS 6.2
Vertical Datum: NAVD88
Projection: NAD 1983 StatePlane West Virginia S FIPS 4702 (US Feet)
Terrain: 1-meter LIDAR (FEMA Region III 3DEP collected 2016-2018)
Land Use: 2019 NLCD
Hydrologic Method:
WV SIR2010-5033 regression equations
Additional Model Notes:
None
END DESCRIPTION:
DSS Export Rating Curves= 0
DSS Export Rating Curve Sorted= 0
DSS Export Volume Flow Curves= 0
DXF OffsetX= 0
DXF OffsetY= 0
DXF ScaleX= 0
DXF ScaleY= 0

--- UPTROUTRN.p01 (plan) ---

Plan Title=Floodplain
Program Version=6.20
Short Identifier=Floodplain
Geom File=g01
Flow File=f01
Subcritical Flow
K Sum by GR= 0
Std Step Tol= 0.01
Critical Tol= 0.01
Num of Std Step Trials= 20
Max Error Tol= 0.3
Flow Tol Ratio= 0.001
Split Flow NTrial= 30
Split Flow Tol= 0.02
Split Flow Ratio= 0.02
Log Output Level= 0
Friction Slope Method= 1
Unsteady Friction Slope Method= 2
Unsteady Bridges Friction Slope Method= 1
Parabolic Critical Depth
Global Vel Dist= 0 , 0 , 0
Global Log Level= 0
CheckData=True
Encroach Param=-1 ,0,0, 0
Mapping Interval=1HOUR
Computation Time Step Use Courant=        0
Computation Time Step Use Time Series=    0
Computation Time Step Count To Double=0
Computation Time Step Max Doubling=0
Computation Time Step Max Halving=0
Computation Time Step Residence Courant=0
Run HTab= 0
Run UNet= 0
Run Sediment= 0
Run PostProcess= 0
Run WQNet= 0
Run RASMapper=-1
UNET Theta= 0
UNET Theta Warmup= 0
UNET ZTol= 0
UNET ZSATol= 0
UNET MxIter= 0
UNET Max Iter WO Improvement= 0
UNET MaxInSteps= 0
UNET DtIC= 0
UNET DtMin= 0
UNET MaxCRTS= 0
UNET WFStab= 0
UNET SFStab= 0
UNET WFX= 1
UNET SFX= 1
UNET Gravity=32.174
UNET 1D Methodology=Finite Difference
UNET DSS MLevel= 1
UNET Pardiso=0
UNET DZMax Abort= 0
UNET Use Existing IB Tables= 0
UNET Froude Reduction=False
UNET Froude Limit= 0
UNET Froude Power= 0
UNET D1 Cores= 0
UNET WindReference=Eulerian
UNET WindDragFormulation=Hsu (1988)
UNET D2 Coriolis=0
UNET D2 Cores= 0
UNET D2 Theta= 1
UNET D2 Theta Warmup= 1
UNET D2 Z Tol= 0.01
UNET D2 Volume Tol= 0.01
UNET D2 Max Iterations= 20
UNET D2 Equation= 0
UNET D2 RampUpFraction=0.1
UNET D2 TimeSlices= 1
UNET D2 Turbulence Formulation=Non-Conservative (original)
UNET D2 Eddy Viscosity=0.3
UNET D2 Transverse Eddy Viscosity=0.1
UNET D2 Smagorinsky Mixing=0
UNET D2 BCVolumeCheck=0
UNET D2 Cores=0
UNET D2 SolverType=PARDISO (Direct)
UNET D2 Minimum Iterations= 2147483647
UNET D2 Maximum Iterations= 2147483647
UNET D2 Restart Number= 10
UNET D2 Relaxation Coeff=1.3
UNET D2 SOR Precondition Iterations= 10
UNET D2 ILUT Maximum Fill= 8
UNET D2 ILUT Tolerance=1E-08
UNET D1D2 MaxIter= 0
UNET D1D2 ZTol=0.01
UNET D1D2 QTol=0.1
UNET D1D2 MinQTol=1
Write IC File= 0
Write IC File at Fixed DateTime=0
Write IC File at Sim End=0
Echo Input=False
Echo Parameters=False
Echo Output=False
Write Detailed= 0
HDF Write Warmup=0
HDF Write Time Slices=0
HDF Flush=0
HDF Compression= 1
HDF Chunk Size= 1
HDF Spatial Parts= 1
HDF Use Max Rows=0
HDF Fixed Rows= 1
Calibration Method= 0
Calibration Iterations= 20
Calibration Max Change=0.05
Calibration Tolerance=0.2
Calibration Maximum=1.5
Calibration Minimum=0.5
Calibration Optimization Method= 1
WQ AD Non Conservative
WQ ULTIMATE=-1
WQ Max Comp Step=1HOUR
WQ Output Interval=15MIN
WQ Output Selected Increments= 0
WQ Output face flow=0
WQ Output face velocity=0
WQ Output face area=0
WQ Output face dispersion=0
WQ Output cell volume=0
WQ Output cell surface area=0
WQ Output cell continuity=0
WQ Output cumulative cell continuity=0
WQ Output face conc=0
WQ Output face dconc_dx=0
WQ Output face courant=0
WQ Output face peclet=0
WQ Output face adv mass=0
WQ Output face disp mass=0
WQ Output cell mass=0
WQ Output cell source sink temp=0
WQ Output nsm pathways=0
WQ Output nsm derived pathways=0
WQ Create Restart=0
WQ Fixed Restart=0
WQ System Summary=0
WQ Write To DSS=0
Sorting and Armoring Iterations= 10
XS Update Threshold= 0.02
Bed Roughness Predictor= 0
Hydraulics Update Threshold= 0.02
Energy Slope Method= 1
Volume Change Method= 1
Sediment Retention Method= 0
Sediment TS Multiplier= 1
Warm Up Method= 0
XS Weighting Method= 0
Number of US Weighted Cross Sections= 1
Number of DS Weighted Cross Sections= 1
Upstream XS Weight=0
Main XS Weight=1
Downstream XS Weight=0
Number of DS XS's Weighted with US Boundary= 1
Upstream Boundary Weight= 1
Weight of XSs Associated with US Boundary= 0
Number of US XS's Weighted with DS Boundary= 1
Downstream Boundary Weight= 0.5
Weight of XSs Associated with DS Boundary= 0.5
Percentile Method= 0
Sediment Output Level= 3
Mass or Volume Output= 0
Output Increment Type= 1
Profile and TS Output Increment= 1
Transport Output Increment 1
XS Output Flag= 0
XS Output Increment= 10
Read HDF5 Sediment Hotstart= 0
Sediment Hotstart Type= 0
Write Gradation File= 0
Read Gradation Hotstart= 0
Write HDF5 File= 1
Write Binary Output= 1
Write DSS Sediment File= 0
DSS Sediment Output Type= 1
SV Curve= 0
Specific Gage Flag= 0
Subcell Erosion Methods= 0
Subcell Deposition Methods= 0
Advection Scheme= 1
Matrix Solver= 0
Implicit Weighting Factor= 1
Maximum Outer Loop Convergence Iterations= 5
Convergence Maximum Absolute= 0.001
Convergence RMSE= 0.0001
Grain Fractions Max Abs Error= 0.001
Max Subgrid Regions= 1
Max Subgrid Length Scale= 3.402823E+38
Initial Layer Thickness= 3.402823E+38
Min Layer Thickness= 3.402823E+38
Max Layer Thickness= 3.402823E+38
Number of Layers= 5

--- UPTROUTRN.f01 (steady flow) ---

Flow Title=Flow
Program Version=6.20
Number of Profiles= 1
Profile Names=P100yr
River Rch & RM=UPTROUTRN,Main            ,9360
     484
River Rch & RM=UPTROUTRN,Main            ,3947
     655
River Rch & RM=UPTROUTRN,Main            ,2291
     730
Boundary for River Rch & Prof#=UPTROUTRN,Main            , 1
Up Type= 0
Dn Type= 3
Dn Slope=0.03137
DSS Import GetInterval= 0
DSS Import GetPeak= 0
DSS Import FillOption= 0

--- UPTROUTRN.g01 (geometry) ---

Geom Title=Geometry
Program Version=6.20

River Reach=UPTROUTRN       ,Main
Reach XY= 30
     2193591.218      615029.245     2193763.006      615155.634
     2193705.367      615405.982     2193822.728      615518.829
     2193752.242      615698.343     2193791.305      615913.187
     2193593.344      616533.247     2193626.331      616743.317
     2193572.641      617575.739      2193771.86      617667.405
     2193880.193      617918.447     2194015.892      618014.367
     2194032.559      618210.895      2194268.67      618418.881
      2194356.17      618691.103      2194649.92      619076.867
     2194663.462      619260.548     2194748.184      619390.409
     2195101.597      619647.941     2195012.204      620041.432
     2195072.068      620157.476     2195008.393      620468.117
      2194703.81      621184.626        2194914.      621347.735
     2195187.168      621401.836     2195343.271      621531.139
2195723.92121674621600.894963877     2196048.514      621937.572
     2196135.849      622108.478     2196391.699       622150.34

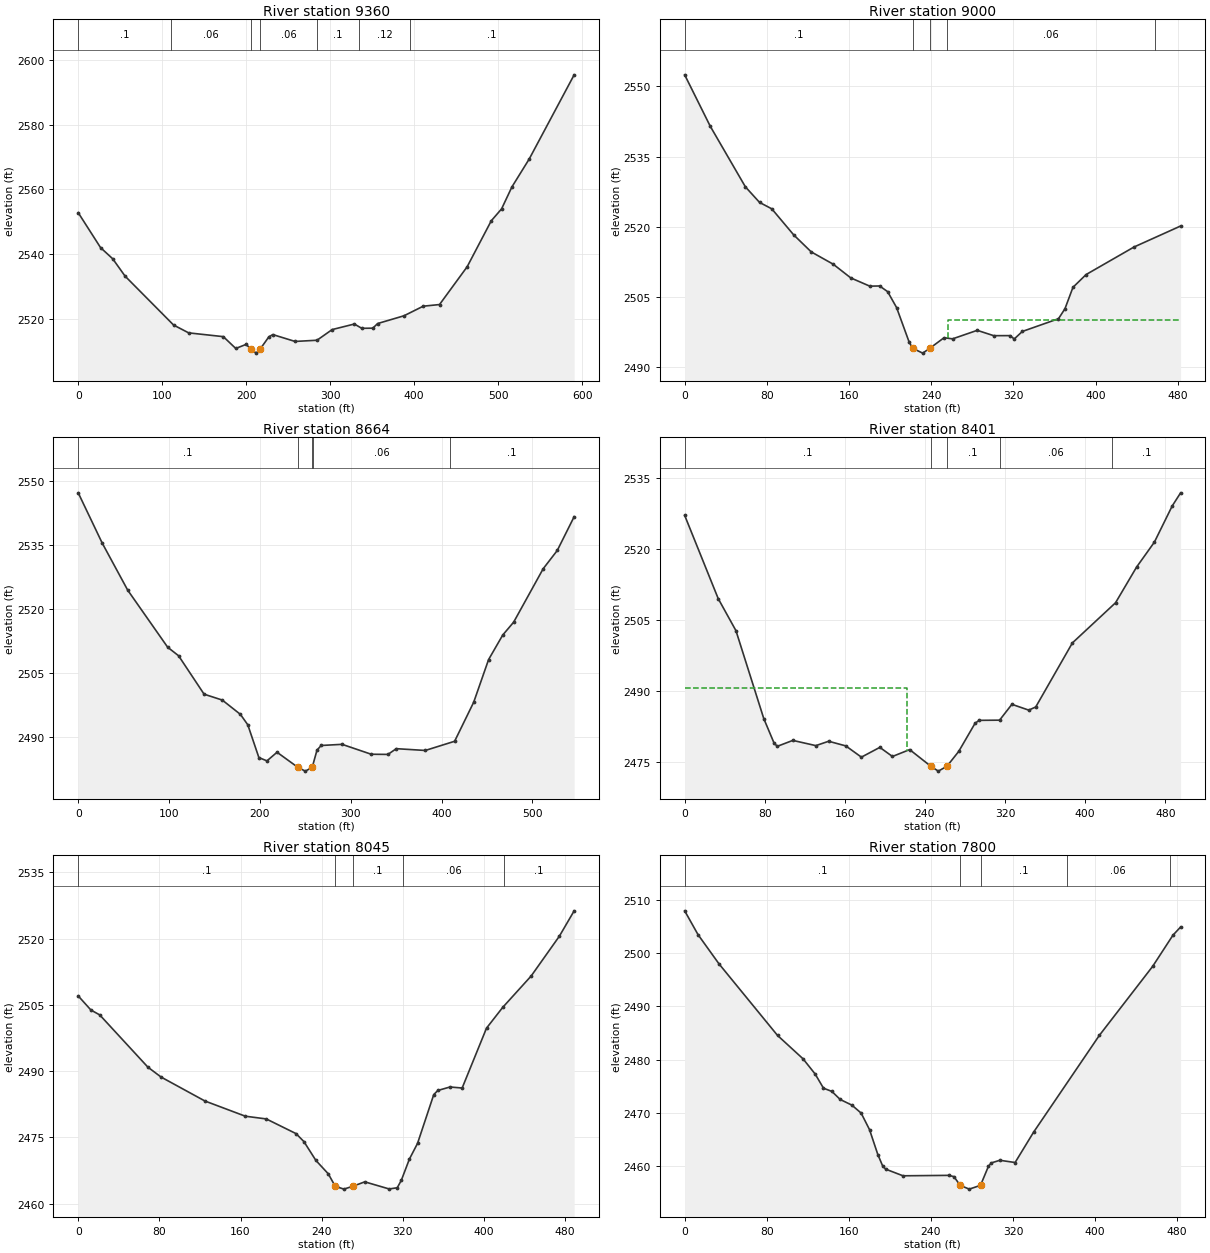
Type RM Length L Ch R = 1 ,9360    ,347.8,360.2,372.2
XS GIS Cut Line= 4
  2193461.802606615183.7675660552193565.23987493615114.372351735
 2193693.9731407 614837.228094072193657.54147621614681.079945392
#Sta/Elev= 30
       0 2552.81    26.6 2542.02    41.1 2538.56    55.8 2533.21   113.6 2518.09
   131.5 2515.68   172.8 2514.51   187.6 2510.86   199.9 2512.12  206.172510.548
     212 2509.42   216.32510.548     227 2514.46   231.7 2515.15   258.2 2513.03
   284.3  2513.4   302.4  2516.7   328.8 2518.41   337.6 2517.09   350.8 2517.13
   356.5 2518.56   387.9 2520.96   410.8 2523.92   430.2 2524.43   463.1  2536.1
   491.8  2550.3   504.1 2553.99   516.4 2560.77     537  2569.4   590.5  2595.4
#Mann= 7 ,-1,0
       0      .1       0     110     .06       0  206.17    .045       0
   216.3     .06       0  284.56      .1       0  334.56     .12       0
  394.56      .1       0
Bank Sta=206.17,216.3
XS Rating Curve= 0 ,0
Exp/Cntr=0.3,0.1

Type RM Length L Ch R = 1 ,9000    ,335.9,335.9,333.6
XS GIS Cut Line= 5
2193524.88315596615323.9037552712193679.88230864615265.372606708
 2193757.5943551615315.5785220522193857.36376401615317.922110339
2193974.79560745615275.584607253
#Sta/Elev= 30
       0 2552.48    24.9 2541.49    59.1 2528.55    72.9 2525.22    84.8 2523.85
   106.1 2518.29   123.2 2514.65   144.6 2512.02   161.7 2509.09   180.2 2507.33
   189.8 2507.37   197.6 2506.15   206.3 2502.75   218.4 2495.45   221.92494.056
   231.7 2493.02   238.72494.067   252.5 2496.31   260.8 2496.07   284.8 2497.89
   300.8 2496.75   316.8 2496.76   320.8 2496.04   328.7 2497.65   363.9 2500.37
   370.2  2502.5     378 2507.08   390.8 2509.81   437.5  2515.7   482.8 2520.18
#Mann= 5 ,-1,0
       0      .1       0   221.9    .045       0   238.7      .1       0
  255.68     .06       0     458      .1       0
#XS Ineff= 2 , 0
                         256.067            2500
Permanent Ineff=
       F       F
Bank Sta=221.9,238.7
XS Rating Curve= 0 ,0
Exp/Cntr(USF)=0,0
Exp/Cntr=0.3,0.1

Type RM Length L Ch R = 1 ,8664    ,266.4,262.2,255
XS GIS Cut Line= 4
2193565.80662949615524.4537615952193764.43468761615535.381285382
2193958.44721939 615644.74116221 2194082.7614997615644.630149159
#Sta/Elev= 30
       0 2547.32    26.4 2535.51    54.5 2524.43    98.5 2511.01   110.5 2509.01
   138.6 2499.97   158.6 2498.59   178.6 2495.22   186.7 2492.77   198.9 2485.07
   207.8 2484.29   218.9 2486.32  242.03 2482.74     250 2481.88  257.592482.739
   262.9 2486.83   267.5 2487.91   290.5 2488.18   322.6 2485.85     341 2485.81
   350.2 2487.16   382.1 2486.74   414.4  2488.9   435.4 2498.08   451.8 2508.11
   467.4 2513.89   479.4 2516.91   511.9 2529.47   527.4 2533.76     546 2541.71
#Mann= 5 ,-1,0
       0      .1       0  242.03    .045       0  257.59      .1       0
  258.93     .06       0  408.93      .1       0
Bank Sta=242.03,257.59
XS Rating Curve= 0 ,0
Exp/Cntr=0.3,0.1

Type RM Length L Ch R = 1 ,8401    ,356.9,356.5,359.1
XS GIS Cut Line= 5
2193559.19172658615716.5699281772193638.86650592615760.968025268
2193763.87734918615807.053494448 2193864.1470356615786.733392984
 2194015.6668667615860.477879039
#Sta/Elev= 30
       0  2527.1    33.5 2509.54    51.2 2502.79      79 2484.24    89.4 2479.01
    92.6  2478.4     108 2479.64     131 2478.54   143.8 2479.46   160.9 2478.48
   176.5 2476.11   194.9 2478.17   207.5 2476.25   224.7  2477.7     2462474.159
   253.3 2473.16   261.92474.181   273.7 2477.32     290 2483.25   294.1 2483.87
   314.5 2483.91   326.8 2487.25   343.6 2486.03   350.6 2486.69   387.2  2500.2
   430.3 2508.67   451.3 2516.19   469.1 2521.46   486.9 2529.09   495.3 2531.86
#Mann= 5 ,-1,0
       0      .1       0     246    .045       0   261.9      .1       0
  314.45     .06       0  426.75      .1       0
#XS Ineff= 2 , 0
          221.88 2490.68
Permanent Ineff=
       F       F
Bank Sta=246,261.9
XS Rating Curve= 0 ,0
Exp/Cntr=0.3,0.1

Type RM Length L Ch R = 1 ,8045    ,235.5,244.4,248.1
XS GIS Cut Line= 3
2193452.58012156616061.9135895442193637.53240223616137.609003518
 2193926.5047886616132.686046381
#Sta/Elev= 30
       0 2507.04    12.5 2503.85    21.2 2502.74    68.7 2490.91    81.7 2488.67
   124.9 2483.25   164.7 2479.81   185.4 2479.19   214.7 2475.87   222.5 2474.06
   234.3  2469.8   246.5 2466.77  253.342463.954   261.9  2463.3   271.3 2463.99
   282.5 2464.95   306.5 2463.34   314.5 2463.61   318.5 2465.28   326.5 2470.11
   334.5 2473.65   350.5  2484.7   354.5 2485.63   366.5 2486.42   378.5 2486.19
   402.5 2499.74   418.5 2504.45   446.5 2511.54   474.3 2520.55   488.9  2526.3
#Mann= 5 ,-1,0
       0      .1       0  253.34    .045       0   271.3      .1       0
  319.84     .06       0  419.84      .1       0
Bank Sta=253.34,271.3
XS Rating Curve= 0 ,0
Exp/Cntr=0.3,0.1

Type RM Length L Ch R = 1 ,7800    ,216.7,211.5,205.8
XS GIS Cut Line= 4
2193415.40822994616286.4159760882193601.84077722 616323.26892148
2193716.73525403616407.8139138492193867.39876607616413.233464642
#Sta/Elev= 30
       0 2507.88      13 2503.42    33.4 2497.95    90.5 2484.52   115.4 2480.13
   127.2 2477.28   135.3 2474.63   143.5 2474.02   151.6 2472.51     163 2471.45
     172 2469.96   180.2 2466.85   188.3 2462.18   192.9 2460.09   195.9 2459.45
   212.8  2458.2   257.5 2458.28   262.5 2458.04  268.552456.406   277.4  2455.7
  288.372456.407   296.1 2459.97   298.9 2460.61   307.2 2461.11   322.1 2460.69
   340.1 2466.37   404.2 2484.52   456.2 2497.47     476 2503.32483.4496 2504.85
#Mann= 5 ,-1,0
       0      .1       0  268.55    .045       0  288.37      .1       0
  372.69     .06       0  472.69      .1       0
Bank Sta=268.55,288.37
XS Rating Curve= 0 ,0
Exp/Cntr(USF)=0,0
Exp/Cntr=0.3,0.1

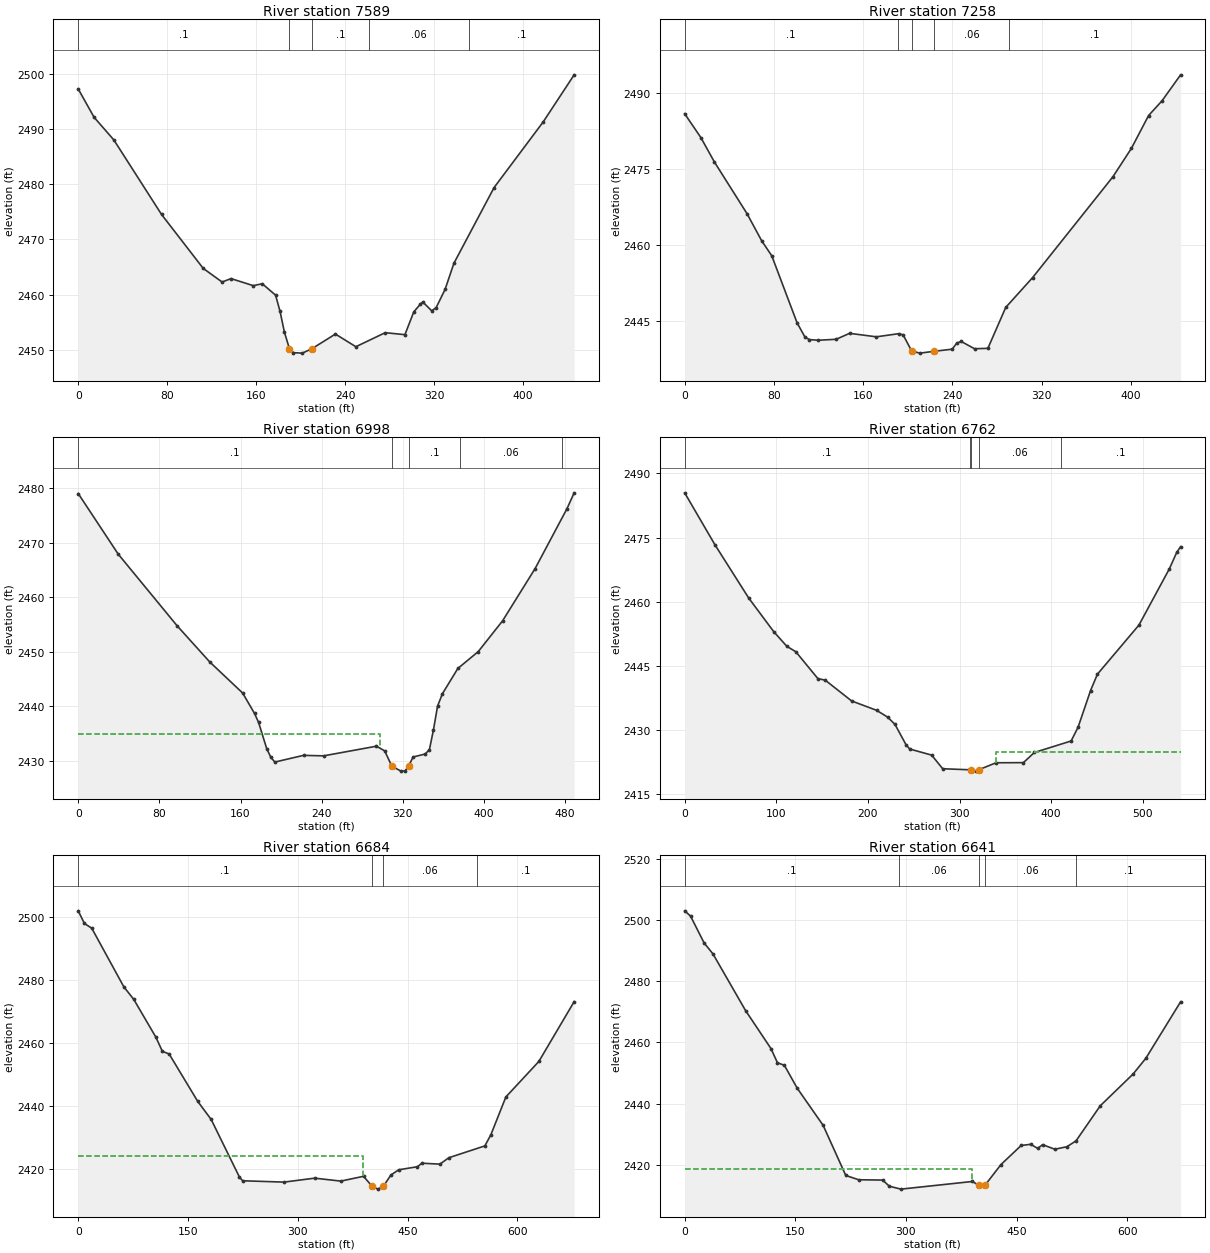
Type RM Length L Ch R = 1 ,7589    ,330.8,330.8,329.8
XS GIS Cut Line= 3
2193411.37343806616505.682710505 2193520.2418162616559.457866699
2193843.96615971616583.352311792
#Sta/Elev= 30
       0 2497.21    14.3 2492.08    32.1 2487.97    74.9 2474.51   112.4 2464.74
   129.4 2462.27   137.4 2462.89   157.5 2461.61   165.5 2461.96   177.5 2459.89
   181.5 2456.96   185.5 2453.15  189.95  2450.2   193.6 2449.48   201.6  2449.4
  210.182450.201   231.3 2452.85   249.7 2450.56   276.1  2453.1   293.8 2452.74
   301.8 2456.87   307.8 2458.29   309.9 2458.65   317.9 2457.06   321.9 2457.64
   329.9 2460.92   337.9 2465.68     374 2479.37   418.2 2491.26     446 2499.77
#Mann= 5 ,-1,0
       0      .1       0  189.95    .045       0  210.18      .1       0
  261.43     .06       0  351.43      .1       0
Bank Sta=189.95,210.18
XS Rating Curve= 0 ,0
Exp/Cntr=0.3,0.1

Type RM Length L Ch R = 1 ,7258    ,259.2,260.1,259.4
XS GIS Cut Line= 3
2193373.13573376616837.0423366452193465.26809724616878.230922671
2193808.86761751616890.153934416
#Sta/Elev= 30
       0 2485.96    14.5 2481.24    26.6 2476.42    55.9 2466.17      69 2460.82
    78.1 2457.82   100.8 2444.55   107.8 2441.75   111.8 2441.23   119.8  2441.1
   135.8 2441.29   147.9 2442.47   171.9 2441.78   191.9  2442.4   195.9 2442.16
  203.63 2438.94     211 2438.55   223.9 2438.92   239.9 2439.33   243.9 2440.51
   247.9 2440.87   259.9 2439.42   271.9  2439.5   287.9  2447.6     312 2453.51
     384 2473.47   400.6  2479.1     416  2485.6     428  2488.5444.7264 2493.66
#Mann= 5 ,-1,0
       0      .1       0  190.92     .06       0  203.63    .045       0
   223.9     .06       0  290.92      .1       0
Bank Sta=203.63,223.9
XS Rating Curve= 0 ,0
Exp/Cntr(USF)=0,0
Exp/Cntr=0.3,0.1

Type RM Length L Ch R = 1 ,6998    ,234.9,236.3,235.7
XS GIS Cut Line= 3
2193282.08728044617099.3485950212193375.30355408617125.362438827
2193766.59512132617150.292372474
#Sta/Elev= 30
       0 2479.01    39.5 2467.89    97.7 2454.73   129.7 2448.14   162.1 2442.45
   173.8 2438.71   177.8 2437.06   185.8 2432.27   189.8  2430.7   193.8  2429.8
   222.1 2431.03   241.9 2430.94     294 2432.71   302.1 2431.85  309.152429.049
   318.1 2428.14   322.1 2428.16   325.62429.049   330.1 2430.73   342.1 2431.28
   346.2 2432.09   350.2 2435.72   354.2 2440.04     359 2442.32   374.2 2446.95
   394.3 2450.04   418.3 2455.68   450.4 2465.27   481.8 2476.24 488.863 2479.14
#Mann= 5 ,-1,0
       0      .1       0  309.15    .045       0   325.6      .1       0
  376.78     .06       0  476.78      .1       0
#XS Ineff= 2 , 0
        297.1779    2435
Permanent Ineff=
       F       F
Bank Sta=309.15,325.6
XS Rating Curve= 0 ,0
Exp/Cntr(USF)=0,0
Exp/Cntr=0.3,0.1

Type RM Length L Ch R = 1 ,6762    ,84,78.3,70.1
BEGIN DESCRIPTION:
Structure XS 4
END DESCRIPTION:
XS GIS Cut Line= 4
2193243.17258656617382.8649816862193473.72259647617366.424058095
2193666.40912713  617374.46447172193780.35019747617346.351586557
#Sta/Elev= 30
       0 2485.47    33.1 2473.28    69.9 2460.82    97.2 2452.95   111.5 2449.52
   121.3 2448.25   145.4 2441.95   153.4 2441.59   182.2 2436.72   209.5 2434.52
   221.6 2432.92   229.6 2431.21   241.6 2426.46   245.6 2425.46   269.6 2424.03
   281.6 2420.84     313 2420.58   317.7 2420.28   320.7 2420.58   339.9 2422.24
   369.7 2422.27   381.7 2424.65   421.8 2427.34   429.4 2430.58     443 2439.15
   450.5 2442.99   495.8 2454.49     529 2467.66     537  2471.5   541.3 2472.86
#Mann= 5 ,-1,0
       0      .1       0  311.14     .06       0     313    .045       0
   320.7     .06       0  411.14      .1       0
#XS Ineff= 2 , 0
                          339.64         2424.87
Permanent Ineff=
       F       F
Bank Sta=313,320.7
XS Rating Curve= 0 ,0
Exp/Cntr=0.5,0.3

Type RM Length L Ch R = 1 ,6684    ,41.4,42.9,45.2
BEGIN DESCRIPTION:
Structure XS 3
END DESCRIPTION:
XS GIS Cut Line= 6
 2193283.3345256617684.691474033 2193535.6700522617570.905343845
2193529.56099497617480.0929250382193561.58736262617432.771726106
2193575.13008705617396.3659520952193783.23880095 617349.66042114
#Sta/Elev= 30
       0 2502.03     8.5 2498.02    18.5 2496.51    62.4 2477.89    75.9 2473.93
   106.1 2461.94     115 2457.45   124.3 2456.59   163.3 2441.56   181.7 2435.82
   220.3 2417.54   224.7 2416.36   281.3 2415.94   323.1 2417.19   358.9 2416.26
   389.9 2417.78  401.58 2414.62   409.5 2413.71  417.03 2414.62   427.3 2418.19
     438 2419.85   463.6 2420.82   469.6 2421.94   494.2 2421.64   506.5 2423.68
   555.7 2427.43   563.9 2430.97   584.4 2442.96   629.5 2454.24   677.7 2473.21
#Mann= 4 ,-1,0
       0      .1       0  401.58    .045       0  417.03     .06       0
  544.43      .1       0
#XS Ineff= 2 , 0
          389.68 2424.32
Permanent Ineff=
       F       F
Bank Sta=401.58,417.03
XS Rating Curve= 0 ,0
Exp/Cntr(USF)=0,0
Exp/Cntr=0.5,0.3

Type RM Length L Ch R = 1 ,6641    ,118.3,115.8,115.7
BEGIN DESCRIPTION:
Structure XS 2
END DESCRIPTION:
XS GIS Cut Line= 6
  2193296.949182617712.6648991582193564.31920379617592.657598545
2193558.21014656617501.8451797382193590.23651421617454.523980806
2193603.77923864617418.1182067952193790.11385605617373.486399315
#Sta/Elev= 30
       0 2502.97     7.9 2501.27    26.3  2492.5    38.4 2488.88    82.5 2470.41
     117 2457.97   125.7 2453.38   135.2 2452.49   152.6 2445.02   187.7  2432.9
   218.4 2416.53   235.9 2415.13   268.4 2415.03   277.4 2413.02   293.1 2412.07
   390.1 2414.57  398.94 2413.28   406.9 2413.27   428.7 2420.08   456.1 2426.32
   468.9 2426.71   478.6 2425.39   485.2  2426.6   501.7  2425.1   518.1 2425.91
   530.5 2427.83   563.4  2439.3   607.9 2449.67   625.1 2454.79   672.3 2473.26
#Mann= 5 ,-1,0
       0      .1       0     290     .06       0  398.94    .045       0
   406.9     .06       0  530.69      .1       0
#XS Ineff= 2 , 0
          389.68 2418.64
Permanent Ineff=
       F       F
Bank Sta=398.94,406.9
XS Rating Curve= 0 ,0
Exp/Cntr(USF)=0,0
Exp/Cntr=0.5,0.3

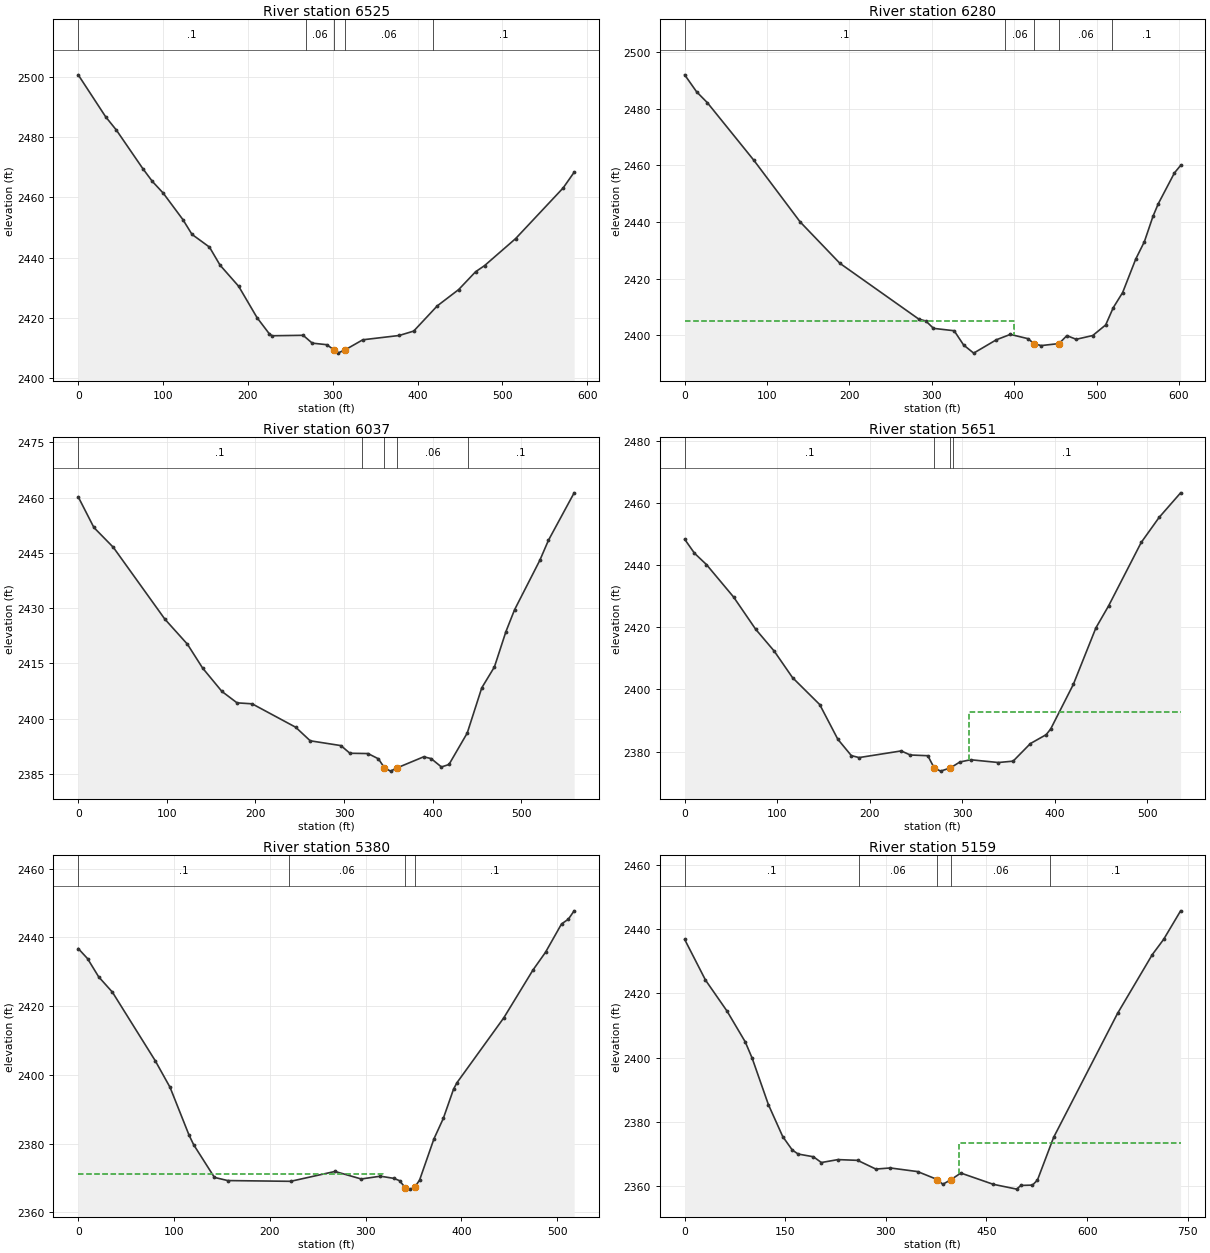
Type RM Length L Ch R = 1 ,6525    ,237.2,245.2,246.6
BEGIN DESCRIPTION:
Structure XS 1
END DESCRIPTION:
XS GIS Cut Line= 4
2193313.73745707617736.1458131852193509.81680476617666.883954052
2193702.96959501617492.2660275062193804.42358586617435.685917228
#Sta/Elev= 30
       0 2500.67    32.3 2486.75      45 2482.31    76.3 2469.46    87.4 2465.27
   100.2 2461.38   123.4 2452.58   134.1 2447.68   154.7 2443.45   167.2 2437.45
   189.1 2430.44   210.8 2420.01     225 2414.74   228.4 2414.01   265.1 2414.16
   275.8 2411.56     293 2411.04  301.142409.384   305.9 2408.24  314.922409.385
   335.4 2412.67   378.3  2414.1   395.4 2415.56   423.2 2423.94   448.4 2429.35
   468.3 2435.26   478.9  2437.3   515.5 2446.27   571.5 2463.09584.5005 2468.32
#Mann= 5 ,-1,0
       0      .1       0  267.95     .06       0  301.14    .045       0
  314.92     .06       0  417.95      .1       0
Bank Sta=301.14,314.92
XS Rating Curve= 0 ,0
Exp/Cntr(USF)=0,0
Exp/Cntr=0.3,0.1

Type RM Length L Ch R = 1 ,6280    ,236.8,242.3,242.7
XS GIS Cut Line= 3
2193406.86699902617907.9189003862193681.93336299617790.458128743
2193913.88121586617595.681406146
#Sta/Elev= 30
       0 2491.95    14.5 2485.95    27.5 2482.13    84.1 2461.75   140.2 2440.04
   188.4 2425.44   284.1 2405.77   292.8 2405.07     302 2402.49   327.1 2401.65
   338.6 2396.61   350.8 2393.75   378.3 2398.46   395.3 2400.36   416.9 2398.84
   423.7 2397.14   432.6 2396.41   454.4 2397.12   463.9 2399.93   475.2 2398.63
   495.3 2399.96     511 2403.69   520.2 2409.78   531.6 2415.13   547.5 2426.94
     558 2433.08   568.5 2442.07   574.8 2446.43   594.5 2457.35601.9786 2459.99
#Mann= 5 ,-1,0
       0      .1       0   389.1     .06       0   423.7    .045       0
   454.4     .06       0   519.1      .1       0
#XS Ineff= 2 , 0
        399.9375    2405
Permanent Ineff=
       F       F
Bank Sta=423.7,454.4
XS Rating Curve= 0 ,0
Exp/Cntr(USF)=0,0
Exp/Cntr=0.3,0.1

Type RM Length L Ch R = 1 ,6037    ,385.1,386.2,385
XS GIS Cut Line= 2
2193603.37134175618136.1320812212194042.95079847617789.465646725
#Sta/Elev= 30
       0 2460.19    17.7 2451.87    39.7 2446.47    97.8    2427   123.3 2420.19
   140.4 2413.73   162.2 2407.38   179.3 2404.28   196.3 2404.02   245.5 2397.66
   261.9 2393.98   296.5 2392.68   306.7  2390.6   327.1 2390.52   338.8  2389.1
  345.622386.671   352.5 2385.75  360.322386.671     390 2389.64   398.4 2389.15
     410 2386.88   418.5 2387.55   439.1 2396.08   455.5 2408.35   469.8 2414.03
   482.8 2423.62   492.5 2429.53     521 2442.94   530.8 2448.41   559.8 2461.28
#Mann= 5 ,-1,0
       0      .1       0     320     .06       0  345.62    .045       0
  360.32     .06       0     440      .1       0
Bank Sta=345.62,360.32
XS Rating Curve= 0 ,0
Exp/Cntr=0.3,0.1

Type RM Length L Ch R = 1 ,5651    ,271.9,271.5,269
XS GIS Cut Line= 2
2193812.94664375 618380.791817792194250.93094739618071.533677639
#Sta/Elev= 30
       0 2448.29    10.6 2443.79    23.5 2440.16    52.9  2429.7    76.7 2419.36
    96.8 2412.31   116.6 2403.78     146 2395.11   165.6 2383.95   180.2 2378.69
   188.6 2378.06   234.1  2380.2   243.9 2378.89   262.9 2378.66  269.692374.754
   276.7  2373.7  287.382374.754   297.5 2376.63   309.1 2377.36   339.1 2376.47
   355.1 2376.91   373.8 2382.57   390.8 2385.42   395.7 2387.25   420.2  2401.6
   444.6 2419.78   458.4  2426.9   493.6 2447.26   512.9 2455.29   536.2 2463.22
#Mann= 4 ,-1,0
       0      .1       0  269.69    .045       0  287.38     .06       0
     290      .1       0
#XS Ineff= 2 , 0
                           307.1         2392.61
Permanent Ineff=
       F       F
Bank Sta=269.69,287.38
XS Rating Curve= 0 ,0
Exp/Cntr=0.3,0.1

Type RM Length L Ch R = 1 ,5380    ,210.6,220.4,232.4
XS GIS Cut Line= 3
2193968.08547963618599.0537008172194273.04578184618368.118606518
2194376.22635626618280.595388997
#Sta/Elev= 30
       0 2436.75     9.7 2433.83    21.4  2428.5    35.7 2424.06    80.4 2404.13
    95.9 2396.37   115.7  2382.5   120.5 2379.71   142.2 2370.19   156.1 2369.27
   221.8 2369.05   268.1 2371.92   295.5 2369.73   315.5 2370.54   329.8  2369.9
   335.5 2369.23   341.6 2367.16   346.9 2366.78   351.3 2367.34   356.4  2369.4
   371.4 2381.39   381.2 2387.35   391.9 2395.87   395.4 2397.71   444.3 2416.58
   474.8  2430.5   487.9 2435.66   504.6 2443.89   511.7 2445.27   517.8 2447.71
#Mann= 4 ,-1,0
       0      .1       0     220     .06       0   341.6    .045       0
   351.3      .1       0
#XS Ineff= 2 , 0
          317.98 2371.24
Permanent Ineff=
       F       F
Bank Sta=341.6,351.3
XS Rating Curve= 0 ,0
Exp/Cntr=0.3,0.1

Type RM Length L Ch R = 1 ,5159    ,41.9,42.7,41
XS GIS Cut Line= 4
 2194035.0296992618696.1586846082194277.12945462 618521.09319754
2194402.56652739618672.1615995382194605.24526207 618535.62013617
#Sta/Elev= 30
       0 2436.72      31  2424.1    63.1 2414.46    90.3 2404.88   100.7 2399.76
   124.8 2385.39   146.2 2375.43   160.5 2371.24   169.2    2370     192 2369.15
   203.8 2367.36   228.5 2368.27   257.9 2368.04     285 2365.33   306.7 2365.67
   347.4 2364.54   376.9 2362.06   384.9 2360.59  396.88 2362.02   411.8 2364.09
   460.1 2360.59   495.1 2359.09   501.3 2360.24   518.6 2360.34     526  2361.9
   550.1 2375.16   645.4 2413.71   697.3 2432.02   714.1 2436.72   739.5 2445.62
#Mann= 5 ,-1,0
       0      .1       0     260     .06       0   376.9    .045       0
  396.88     .06       0  545.12      .1       0
#XS Ineff= 2 , 0
                          409.53         2373.55
Permanent Ineff=
       F       F
Bank Sta=376.9,396.88
XS Rating Curve= 0 ,0
Exp/Cntr(USF)=0,0
Exp/Cntr=0.3,0.1

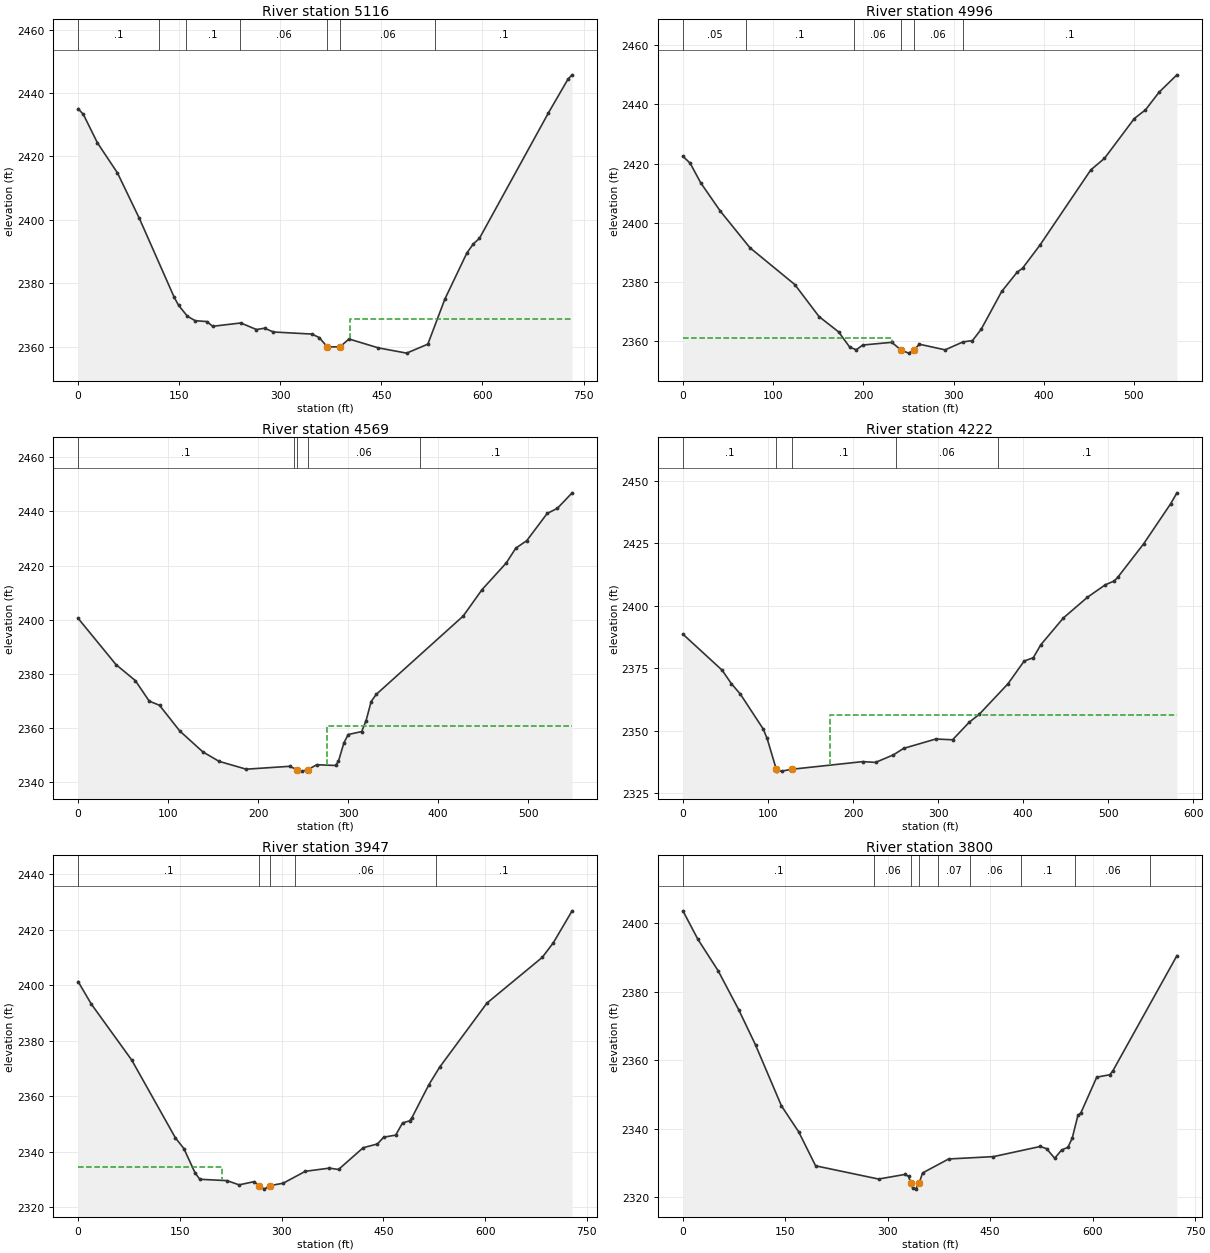
Type RM Length L Ch R = 1 ,5116    ,130.8,120.2,109.1
XS GIS Cut Line= 4
2194048.94932154618708.8903837382194269.74583532618548.311100986
2194395.18290809618699.3795029842194613.19997676618550.908224297
#Sta/Elev= 30
       0 2435.06     7.8 2433.26    28.7 2424.28    58.4 2414.81    90.9 2400.46
   142.4 2375.69   149.1 2373.06   162.3 2369.59   173.9  2368.2   191.1 2367.94
   199.7 2366.44   241.4 2367.49   264.7 2365.42   276.8 2365.84   289.7 2364.65
   346.9 2363.99   357.7  2362.9   369.82359.945   388.72359.976     402 2362.44
   445.7 2359.63   487.5 2357.98     519 2360.81   544.3 2375.04     577 2389.59
   586.7 2392.48   595.5 2394.15     698 2433.76   727.1 2444.42   733.1 2445.74
#Mann= 7 ,-1,0
       0      .1       0     120     .05       0     160      .1       0
     240     .06       0   369.8    .045       0   388.7     .06       0
  529.37      .1       0
#XS Ineff= 2 , 0
                          403.56        2368.727
Permanent Ineff=
       F       F
Bank Sta=369.8,388.7
XS Rating Curve= 0 ,0
Exp/Cntr(USF)=0,0
Exp/Cntr=0.3,0.1

Type RM Length L Ch R = 1 ,4996    ,427.6,427.3,427
XS GIS Cut Line= 2
2194193.84720582618886.4864080782194627.86298668618552.343739876
#Sta/Elev= 30
       0 2422.46       8 2420.13    19.7 2413.51    41.5 2403.93    74.3 2391.59
   124.1 2379.15   150.9 2368.36   172.6 2363.19   185.1 2357.98   192.3 2357.17
   199.4 2358.76   231.6 2359.66  241.992357.014   250.3 2356.02  255.922357.014
   262.1 2359.03   290.7 2357.13   310.6 2359.81     321 2360.25   330.6 2364.03
   353.4 2376.82   370.5 2383.32   376.5 2384.66   395.6 2392.37   452.2 2417.85
   467.4 2421.76   500.5  2435.2   512.8  2438.1   527.9 2444.06   547.7 2449.94
#Mann= 6 ,-1,0
       0     .05       0      70      .1       0     190     .06       0
  241.99    .045       0  255.92     .06       0     310      .1       0
#XS Ineff= 2 , 0
        232.2967    2361
Permanent Ineff=
       F       F
Bank Sta=241.99,255.92
XS Rating Curve= 0 ,0
Exp/Cntr=0.3,0.1

Type RM Length L Ch R = 1 ,4569    ,346.4,346.6,343.1
XS GIS Cut Line= 2
2194456.57971775619237.1585187222194866.94899589618872.881442108
#Sta/Elev= 30
       0 2400.48    42.1 2383.37    63.6 2377.45      79 2369.87    90.4 2368.34
     113 2358.81   138.5 2351.13   156.6 2347.61   186.7 2344.72     235 2345.78
   243.4 2344.52     249    2344  255.05 2344.51   265.1 2346.37   285.9 2346.09
   289.2 2347.67   295.2 2354.41     300 2357.53     315 2358.62   319.9 2362.71
   325.5 2369.73   331.2 2372.38   427.8 2401.34   448.7  2411.1   475.5 2420.91
   486.2 2426.42   498.4  2429.2     521 2439.23   532.4 2441.14548.7264 2446.86
#Mann= 5 ,-1,0
       0      .1       0     240     .06       0   243.4    .045       0
  255.05     .06       0     380      .1       0
#XS Ineff= 2 , 0
                           276.5         2360.58
Permanent Ineff=
       F       F
Bank Sta=243.4,255.05
XS Rating Curve= 0 ,0
Exp/Cntr(USF)=0,0
Exp/Cntr=0.3,0.1

Type RM Length L Ch R = 1 ,4222    ,278.4,275.2,271.4
XS GIS Cut Line= 3
2194657.89613562      619466.7562195017.12036217 619143.48727045
2195053.31534636619052.771619157
#Sta/Elev= 30
       0  2388.7    46.1 2374.31    56.9 2368.95    67.6 2364.71    94.5 2350.74
      99 2347.01  109.782334.702   110.7 2334.05     116 2333.94  128.562334.706
   211.6 2337.75   226.5 2337.43   247.5 2340.44   259.5 2343.03   297.3 2346.78
   317.1 2346.48   336.9 2353.57   348.3 2356.61   382.3 2368.89   401.3 2377.97
     412 2379.29   420.9  2384.5   447.4 2395.19   475.7 2403.47   496.6 2408.43
   507.3    2410   511.6 2411.56   541.7  2424.8   573.6 2440.88   580.9 2445.22
#Mann= 5 ,-1,0
       0      .1       0  109.78    .045       0  128.56      .1       0
     250     .06       0     370      .1       0
#XS Ineff= 2 , 0
                          172.68         2356.57
Permanent Ineff=
       F       F
Bank Sta=109.78,128.56
XS Rating Curve= 0 ,0
Exp/Cntr=0.3,0.1

Type RM Length L Ch R = 1 ,3947    ,143.5,147.2,149.9
XS GIS Cut Line= 4
2194753.47989811619667.1300370172194926.90552349619621.364941433
2195052.15736403619361.2265033752195101.53549348619105.905443799
#Sta/Elev= 30
       0 2401.38    19.3 2393.32    79.1 2373.05   143.4 2345.04   155.9 2341.17
   172.4 2332.41   179.4 2330.11   219.5 2329.62   237.3  2328.1   259.5 2329.26
  266.15 2327.83   274.5 2326.56  282.96 2327.83   302.2 2328.69     335 2332.99
   370.5 2334.13   383.8 2333.64   420.2 2341.49   441.2 2342.84   450.4 2345.29
   468.1 2346.03   478.2 2350.43   488.5 2351.16     492 2352.29     517 2364.21
     533 2370.55   602.6 2393.62   684.1 2410.09   700.4 2415.34728.1358 2426.87
#Mann= 5 ,-1,0
       0      .1       0  266.15    .045       0  282.96      .1       0
  319.36     .06       0  528.08      .1       0
#XS Ineff= 2 , 0
          212.56 2334.56
Permanent Ineff=
       F       F
Bank Sta=266.15,282.96
XS Rating Curve= 0 ,0
Exp/Cntr(USF)=0,0
Exp/Cntr=0.3,0.1

Type RM Length L Ch R = 1 ,3800    ,21.2,21.2,21.1
XS GIS Cut Line= 6
2194759.28762178619707.5034134872194934.11430566 619649.23067598
2195068.49657621619635.2579846432195125.60496653619567.559547246
2195172.13722964619474.4950210312195368.74127683619544.604868399
#Sta/Elev= 30
       0 2403.67      22 2395.32    51.5 2386.17    81.6 2374.78   106.3 2364.46
   144.3 2346.62   169.6    2339   194.3 2329.09   286.5 2325.22   325.4 2326.58
   330.5 2325.97  333.84 2323.92   336.9 2322.49   340.7 2322.27   345.8 2323.94
   350.9    2327   389.1 2331.09   454.8 2331.78   523.2 2334.74   532.5 2334.11
   544.4  2331.3   554.4 2333.69   563.8 2334.52     570 2337.12   578.4 2343.83
   582.7 2344.55     606 2355.02   625.1 2355.73   629.5 2356.84   723.4 2390.56
#Mann= 9 ,-1,0
       0      .1       0  279.56     .06       0  333.84    .045       0
   345.8     .06       0  373.27     .07       0  420.25     .06       0
   494.4      .1       0  574.68     .06       0  684.68      .1       0
Bank Sta=333.84,345.8
XS Rating Curve= 0 ,0
Exp/Cntr=0.3,0.1