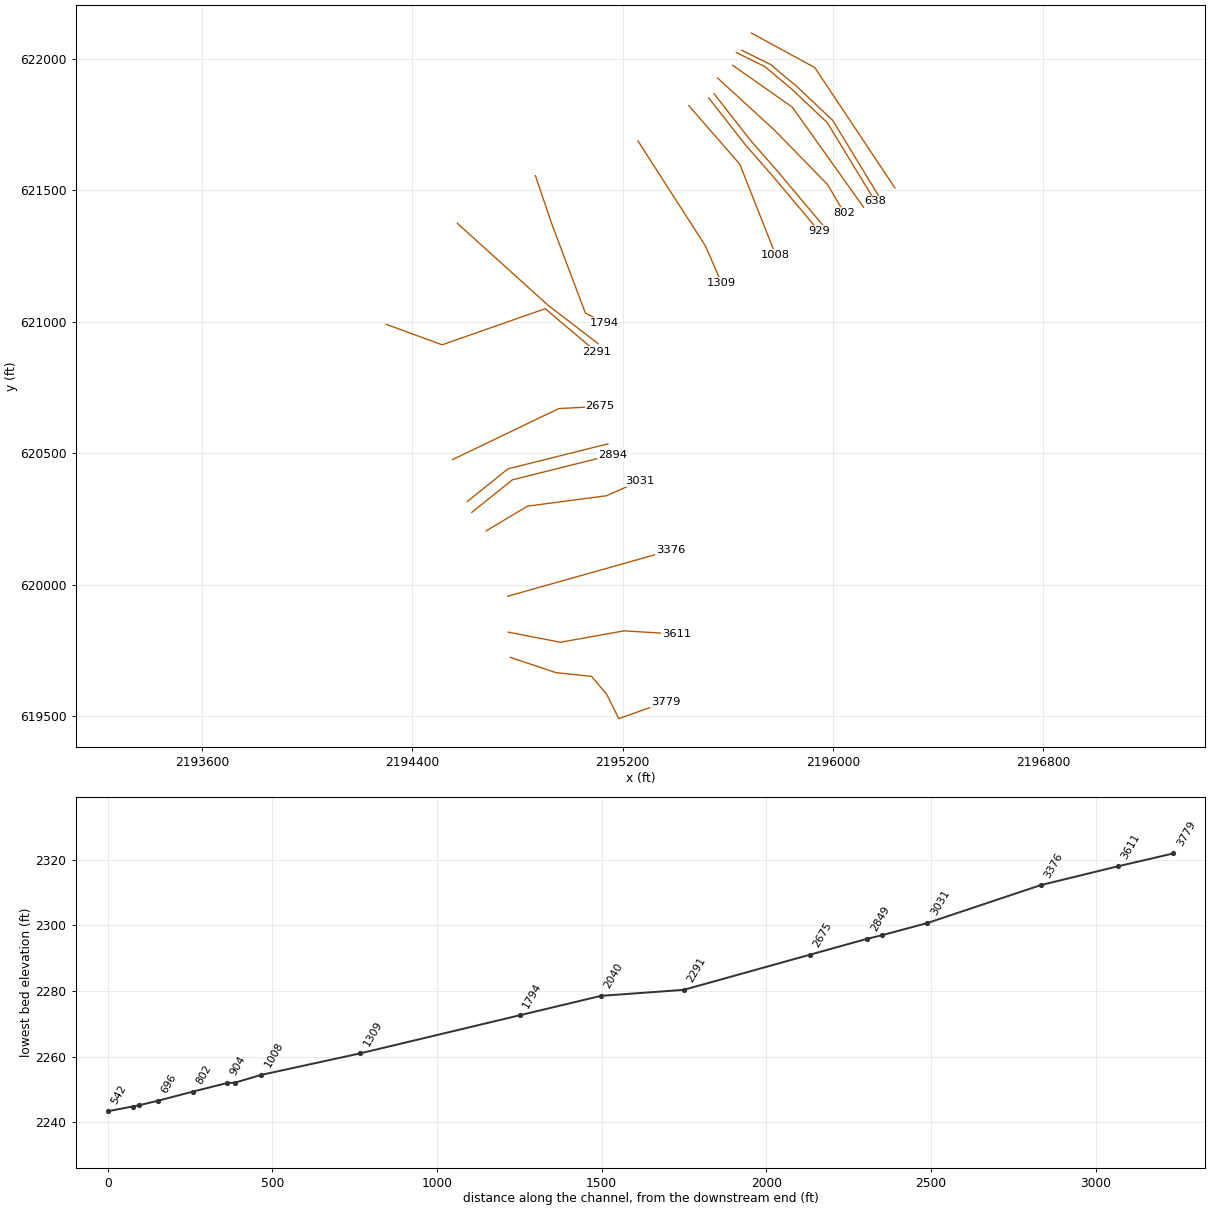
HEC-RAS study UPTROUTRN.prj: UPTROUTRN

--- UPTROUTRN.g01 (geometry) --- (continued)

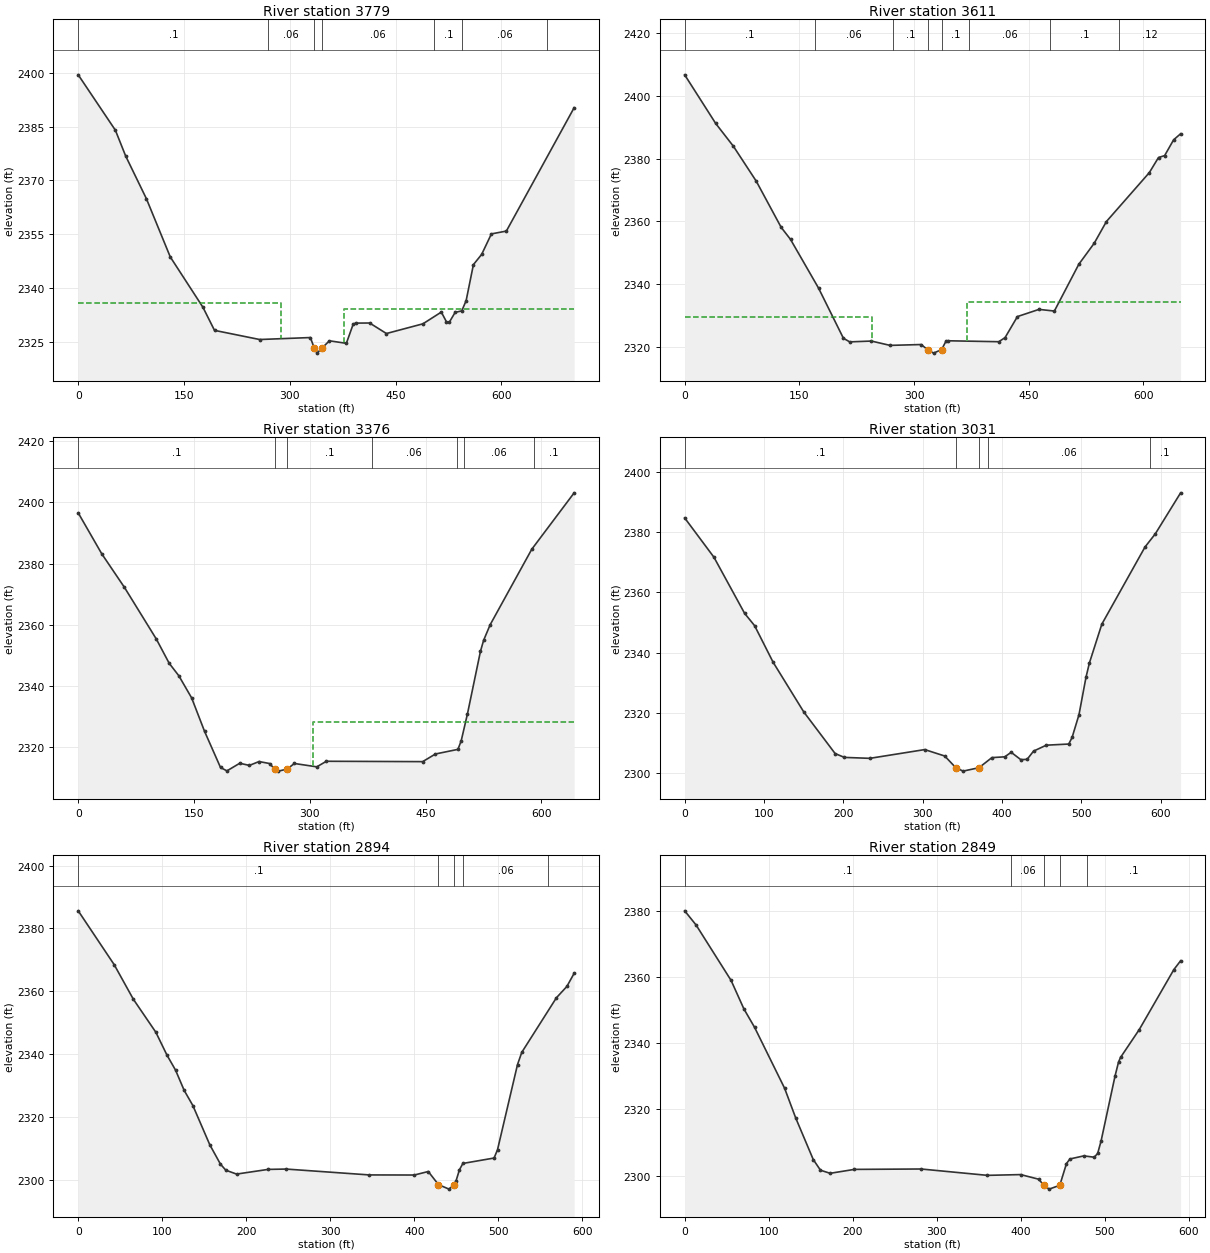
Type RM Length L Ch R = 1 ,3779    ,162.6,167.8,172.9
XS GIS Cut Line= 6
 2194772.4087719619724.0699823132194947.23545578619665.797244806
2195081.61772633619651.8245534692195138.72611665619584.126116071
2195185.25837976619491.0615898562195362.74181319619554.127000577
#Sta/Elev= 30
       0 2399.42    52.7 2383.99    67.2 2376.84    96.7  2364.9   130.5  2348.7
   176.8 2334.68   193.2 2328.25   257.2  2325.7   329.1 2326.25   334.52323.372
   338.6 2321.91  345.81 2323.38   356.1 2325.34   380.1 2324.64   389.8 2329.98
   393.2 2330.27   413.1  2330.3   436.9 2327.37   488.6 2330.07   514.7 2333.34
     522 2330.63   526.3 2330.61   534.3 2333.26   543.7 2333.68   549.9 2336.54
   560.2 2346.56   571.9 2349.41   585.7 2355.12   606.9  2355.9     703 2390.27
#Mann= 7 ,-1,0
       0      .1       0  269.56     .06       0   334.5    .045       0
  345.81     .06       0   504.4      .1       0  544.68     .06       0
  664.68      .1       0
#XS Ineff= 2 , 0
          287.07 2335.83  377.41         2334.14
Permanent Ineff=
       F       F
Bank Sta=334.5,345.81
XS Rating Curve= 0 ,0
Exp/Cntr=0.3,0.1

Type RM Length L Ch R = 1 ,3611    ,234.2,235.3,236
XS GIS Cut Line= 4
 2194764.3189997619820.081803839 2194963.0358621619781.542775978
2195205.10913085619824.8991823212195405.03033788619812.855736115
#Sta/Elev= 30
       0 2406.76    40.6 2391.24    63.8 2383.95    93.6 2372.85   126.2 2358.11
   138.4 2354.28   175.1 2338.73   207.6 2322.75   215.8 2321.59   244.2 2321.85
   268.6 2320.47   309.2 2320.74  317.742319.123   325.5    2318  336.032319.124
   341.7 2321.79   344.4 2321.94   410.8 2321.64     419 2322.94   435.2 2329.66
   463.4 2331.95   483.5 2331.42   515.5 2346.35   535.6 2353.04   551.6 2359.98
   607.7 2375.57   619.7 2380.39   627.7 2380.99   639.5 2386.04648.6284 2387.96
#Mann= 8 ,-1,0
       0      .1       0     170     .06       0  272.42      .1       0
  317.74    .045       0  336.03      .1       0  372.42     .06       0
  478.34      .1       0  568.34     .12       0
#XS Ineff= 2 , 0
          244.62 2329.65  369.76          2334.2
Permanent Ineff=
       F       F
Bank Sta=317.74,336.03
XS Rating Curve= 0 ,0
Exp/Cntr(USF)=0,0
Exp/Cntr=0.3,0.1

Type RM Length L Ch R = 1 ,3376    ,341.9,344.5,341.2
XS GIS Cut Line= 2
2194762.79082833619956.7122674562195381.07869799620130.844917601
#Sta/Elev= 30
       0 2396.58    30.5 2383.21    59.9 2372.24   101.2 2355.36   117.8 2347.47
   130.3 2343.39   146.9 2336.15   163.6 2325.25   184.3 2313.43   192.6 2312.32
   209.2 2314.81   221.7 2314.11   234.2 2315.37   247.9 2314.72   254.4 2312.89
   259.1 2312.24   270.6 2312.89   279.9 2314.74     309 2313.64   321.4 2315.46
   446.1 2315.34   462.7 2317.84   491.8 2319.35     496 2322.13   504.1 2330.92
   520.9 2351.31     525 2354.93   533.5 2360.04   587.4  2384.7   642.3 2403.13
#Mann= 7 ,-1,0
       0      .1       0   254.4    .045       0   270.6      .1       0
     380     .06       0     490     .07       0     500     .06       0
     590      .1       0
#XS Ineff= 2 , 0
                          303.46         2328.18
Permanent Ineff=
       F       F
Bank Sta=254.4,270.6
XS Rating Curve= 0 ,0
Exp/Cntr=0.3,0.1

Type RM Length L Ch R = 1 ,3031    ,137.8,137.3,137.6
XS GIS Cut Line= 4
2194680.56741932620205.0693175522194837.51219156620299.236180894
2195138.18533416620338.8853865122195265.39320219 620395.05509447
#Sta/Elev= 30
       0 2384.62    36.9 2371.59    75.6 2352.98    88.2  2348.9   111.5 2336.79
   150.1 2320.34   189.7 2306.52   201.4 2305.24   233.5 2304.93   302.7 2307.83
   327.9  2305.7   341.9 2301.82   351.1 2300.69  371.13 2301.83   387.4 2305.17
   403.6 2305.43   411.7 2306.93   423.8  2304.5   431.8 2304.59   439.9 2307.32
     456 2309.29   484.3 2309.67   488.5 2311.84   497.2  2319.4     506 2331.75
   510.3 2336.51     526  2349.4   580.5    2375   593.4 2379.33625.3607 2392.94
#Mann= 5 ,-1,0
       0      .1       0   341.9    .045       0  371.13      .1       0
  383.03     .06       0   586.3      .1       0
Bank Sta=341.9,371.13
XS Rating Curve= 0 ,0
Exp/Cntr(USF)=0,0
Exp/Cntr=0.3,0.1

Type RM Length L Ch R = 1 ,2894    ,45.4,44.8,45.3
XS GIS Cut Line= 3
2194625.76607759620275.3900607822194780.61452917620399.456178942
2195160.62305926620494.439462576
#Sta/Elev= 30
       0  2385.6    42.8 2368.46    65.6 2357.45    92.4 2346.93   105.6 2339.66
   115.8 2334.89   126.1 2328.42   136.4 2323.61   156.6 2311.09   169.2 2304.97
   175.6 2303.02   188.4 2301.78   225.9 2303.27   247.4 2303.38   346.4 2301.51
     400 2301.48   416.5  2302.6  428.65 2298.43   441.2 2296.99     4472298.341
   449.5 2299.55   453.6 2303.14   457.7 2305.17   494.8 2306.89   498.9 2309.52
   522.7 2336.65   527.8 2340.55     569 2357.92   581.4 2361.51   590.1 2365.71
#Mann= 5 ,-1,0
       0      .1       0  428.65    .045       0     447      .1       0
  458.42     .06       0  558.42      .1       0
Bank Sta=428.65,447
XS Rating Curve= 0 ,0
Exp/Cntr(USF)=0,0
Exp/Cntr=0.3,0.1

Type RM Length L Ch R = 1 ,2849    ,171.1,173.6,175.2
XS GIS Cut Line= 3
2194609.06651782620317.1657908612194763.91496939620441.231909021
2195143.92349949620536.215192656
#Sta/Elev= 30
       0 2379.96    13.6 2375.67    55.2 2358.95    70.5 2350.32    83.2 2344.76
   118.9 2326.37   132.1 2317.41     153 2304.84   161.6 2301.62   173.1 2300.69
   201.9 2301.87   281.3 2301.99   360.2 2300.07   399.8  2300.3   421.3  2298.9
  427.23  2297.1   433.7 2295.91  446.34 2297.08   454.3 2303.64   458.4 2305.02
   474.9 2305.95   487.3 2305.55   491.4 2306.68   495.5 2310.49     512 2329.99
   516.2 2334.26   518.6 2335.68   540.9  2344.1   582.1 2362.23   590.1 2364.88
#Mann= 5 ,-1,0
       0      .1       0  388.42     .06       0  427.23    .045       0
  446.34     .06       0  478.42      .1       0
Bank Sta=427.23,446.34
XS Rating Curve= 0 ,0
Exp/Cntr(USF)=0,0
Exp/Cntr=0.3,0.1

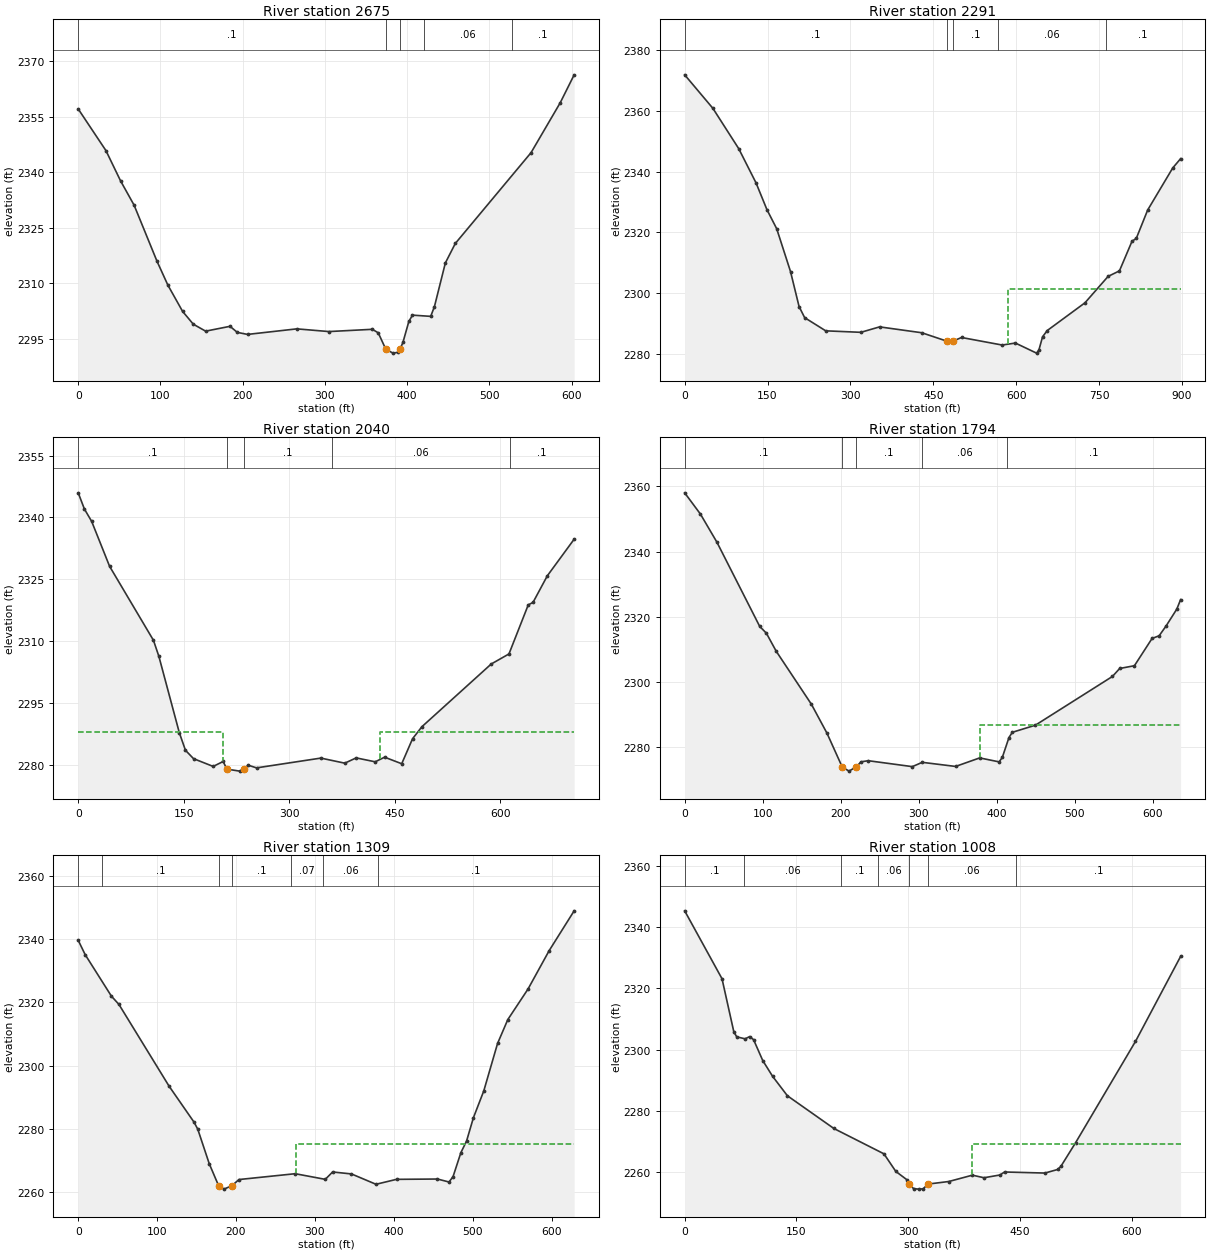
Type RM Length L Ch R = 1 ,2675    ,384.9,384.1,383.4
XS GIS Cut Line= 3
2194553.79242411620476.8385505732194956.88449982620670.392137119
 2195112.5400669620678.685659234
#Sta/Elev= 30
       0 2357.07    33.7 2345.82    51.5 2337.63      68 2331.04    95.8  2315.9
   109.1 2309.41   126.9 2302.35   139.9 2298.89   154.9    2297   184.6 2298.31
   193.4 2296.67   205.9 2296.12   265.8 2297.62   304.8 2296.89   357.6  2297.5
   364.8 2296.55  374.042292.083   382.8 2291.06   388.7 2291.28  391.212292.083
   394.8 2293.94     402 2299.62   406.4 2301.33   428.6    2301   433.1 2303.62
   446.4 2315.44   458.5 2320.71   550.6 2345.26     586 2358.72     603  2366.3
#Mann= 5 ,-1,0
       0      .1       0  374.04    .045       0  391.21      .1       0
     420     .06       0  527.15      .1       0
Bank Sta=374.04,391.21
XS Rating Curve= 0 ,0
Exp/Cntr=0.3,0.1

Type RM Length L Ch R = 1 ,2291    ,260.7,250.9,237.5
XS GIS Cut Line= 4
2194300.35184058620990.941069113 2194513.1444307620913.025318098
2194905.06458674 621050.209816582195100.43579451620885.493272761
#Sta/Elev= 30
       0 2371.82    51.1 2360.79    97.8 2347.55   129.1  2336.3   148.9 2327.48
   166.5 2321.23   191.5 2307.15     207 2295.64   217.1 2291.99   255.2 2287.66
   318.8 2287.17   352.7 2288.96     429 2287.03     474 2284.29  485.61 2284.29
     501 2285.47   574.4 2282.99   598.5 2283.64   636.7 2280.33   640.9 2281.32
   647.6  2285.7   656.1 2287.76   724.3 2296.87   766.2 2305.56   786.7 2307.37
   809.4 2317.09   817.2 2318.05   837.8 2327.38   883.2 2341.22   897.4 2344.26
#Mann= 5 ,-1,0
       0      .1       0     474    .045       0  485.61      .1       0
  566.61     .06       0  761.84      .1       0
#XS Ineff= 2 , 0
                           584.7         2301.37
Permanent Ineff=
       F       F
Bank Sta=474,485.61
XS Rating Curve= 0 ,0
Exp/Cntr=0.3,0.1

Type RM Length L Ch R = 1 ,2040    ,250.1,246.9,239.5
XS GIS Cut Line= 3
2194571.13002983 621375.092286032194914.75647851621064.506842023
2195106.39430567 620917.47437119
#Sta/Elev= 30
       0 2345.98     8.8 2342.05    19.1 2339.06    44.6 2328.16   106.9 2310.23
   114.6 2306.35   143.7 2287.81   152.4 2283.56   163.9 2281.53   191.8 2279.65
     206 2280.85  211.16    2279   229.5 2278.51   235.5 2278.99   241.5 2279.95
   253.4  2279.3   344.8 2281.67   378.8 2280.44     395 2281.72     422 2280.77
   435.4 2281.89   459.7  2280.3   475.1 2286.36   488.4 2289.28   586.9 2304.48
   612.1 2306.92   639.5 2318.81   646.3 2319.42   666.6 2325.86704.7315 2334.74
#Mann= 5 ,-1,0
       0      .1       0  211.16    .045       0   235.5      .1       0
     360     .06       0  613.19      .1       0
#XS Ineff= 2 , 0
          205.63 2287.99428.8823            2288
Permanent Ineff=
       F       F
Bank Sta=211.16,235.5
XS Rating Curve= 0 ,0
Exp/Cntr(USF)=0,0
Exp/Cntr=0.3,0.1

Type RM Length L Ch R = 1 ,1794    ,482.9,485,486
XS GIS Cut Line= 4
2194868.10306911621556.3267722072194930.15406838621372.974636565
  2195058.032201621033.8932710582195128.56165813620996.888977331
#Sta/Elev= 30
       0 2358.05    20.2 2351.52    41.3  2342.9    96.2 2317.01   104.7 2314.95
   117.3 2309.41   162.4 2293.13   182.4 2284.23  201.832273.898   210.6 2272.59
  219.822273.896     226 2275.45   235.3 2275.79   291.7 2273.97   304.5 2275.29
   347.2 2274.03   378.1 2276.65     403 2275.43   407.1 2276.81   415.6  2282.9
   419.9 2284.51   449.5  2286.7   548.2 2301.66   557.5 2304.11   576.4 2304.96
     599 2313.33   608.1 2314.16   617.1 2317.21   630.7 2322.34   635.6 2325.27
#Mann= 5 ,-1,0
       0      .1       0  201.83    .045       0  219.82      .1       0
  303.57     .06       0  413.57      .1       0
#XS Ineff= 2 , 0
                          378.56         2286.63
Permanent Ineff=
       F       F
Bank Sta=201.83,219.82
XS Rating Curve= 0 ,0
Exp/Cntr=0.3,0.1

Type RM Length L Ch R = 1 ,1309    ,298.7,300.4,297.3
XS GIS Cut Line= 3
2195257.90988364621688.5946601162195514.89547561621288.839294835
2195576.08252132 621148.10908971
#Sta/Elev= 30
       0 2339.58     8.8 2335.06    42.1 2321.93    51.6 2319.33   115.1 2293.53
   146.7 2282.17   151.5 2279.94   166.2 2268.94  178.012262.035   184.8 2260.97
  194.732262.035   203.8    2264   275.1 2265.84   313.2 2264.06   322.5 2266.39
   346.4 2265.77   377.5  2262.5   403.5 2264.06   455.4 2264.16   470.1 2263.22
   475.2 2264.94   485.1  2272.5   492.3 2276.16     501 2283.54   514.1 2291.98
   531.6 2306.99   544.6 2314.54   570.2 2324.18     597 2336.31628.6888 2348.89
#Mann= 7 ,-1,0
       0     .06       0      30      .1       0  178.01    .045       0
  194.73      .1       0     270     .07       0     310     .06       0
     380      .1       0
#XS Ineff= 2 , 0
                          275.45         2275.38
Permanent Ineff=
       F       F
Bank Sta=178.01,194.73
XS Rating Curve= 0 ,0
Exp/Cntr(USF)=0,0
Exp/Cntr=0.3,0.1

Type RM Length L Ch R = 1 ,1008    ,77.6,78.8,82.7
XS GIS Cut Line= 3
2195451.39221957621822.950782064 2195645.2917035621600.147027246
2195781.38264563621255.704465744
#Sta/Elev= 30
       0 2345.34    50.1 2323.16      66 2305.78    69.9 2304.16    81.2 2303.52
    87.2 2304.25    92.5 2303.24   104.8 2296.42   118.1 2291.24   137.9 2284.91
   200.3 2274.22   267.5 2265.94   283.4  2260.2   298.6 2257.42  301.732256.057
   307.2 2254.57   314.1 2254.41   320.1 2254.51   326.62256.058   354.5  2256.9
   386.2 2258.97   401.8 2258.13   423.2 2259.03   429.4 2260.01   483.5 2259.66
   500.7 2260.83     505 2261.85   524.9 2269.64   605.1 2302.66665.7148 2330.45
#Mann= 7 ,-1,0
       0      .1       0      80     .06       0     210      .1       0
     260     .06       0  301.73    .045       0   326.6     .06       0
  445.36      .1       0
#XS Ineff= 2 , 0
                        385.6294            2269
Permanent Ineff=
       F       F
Bank Sta=301.73,326.6
XS Rating Curve= 0 ,0
Exp/Cntr(USF)=0,0
Exp/Cntr=0.3,0.1

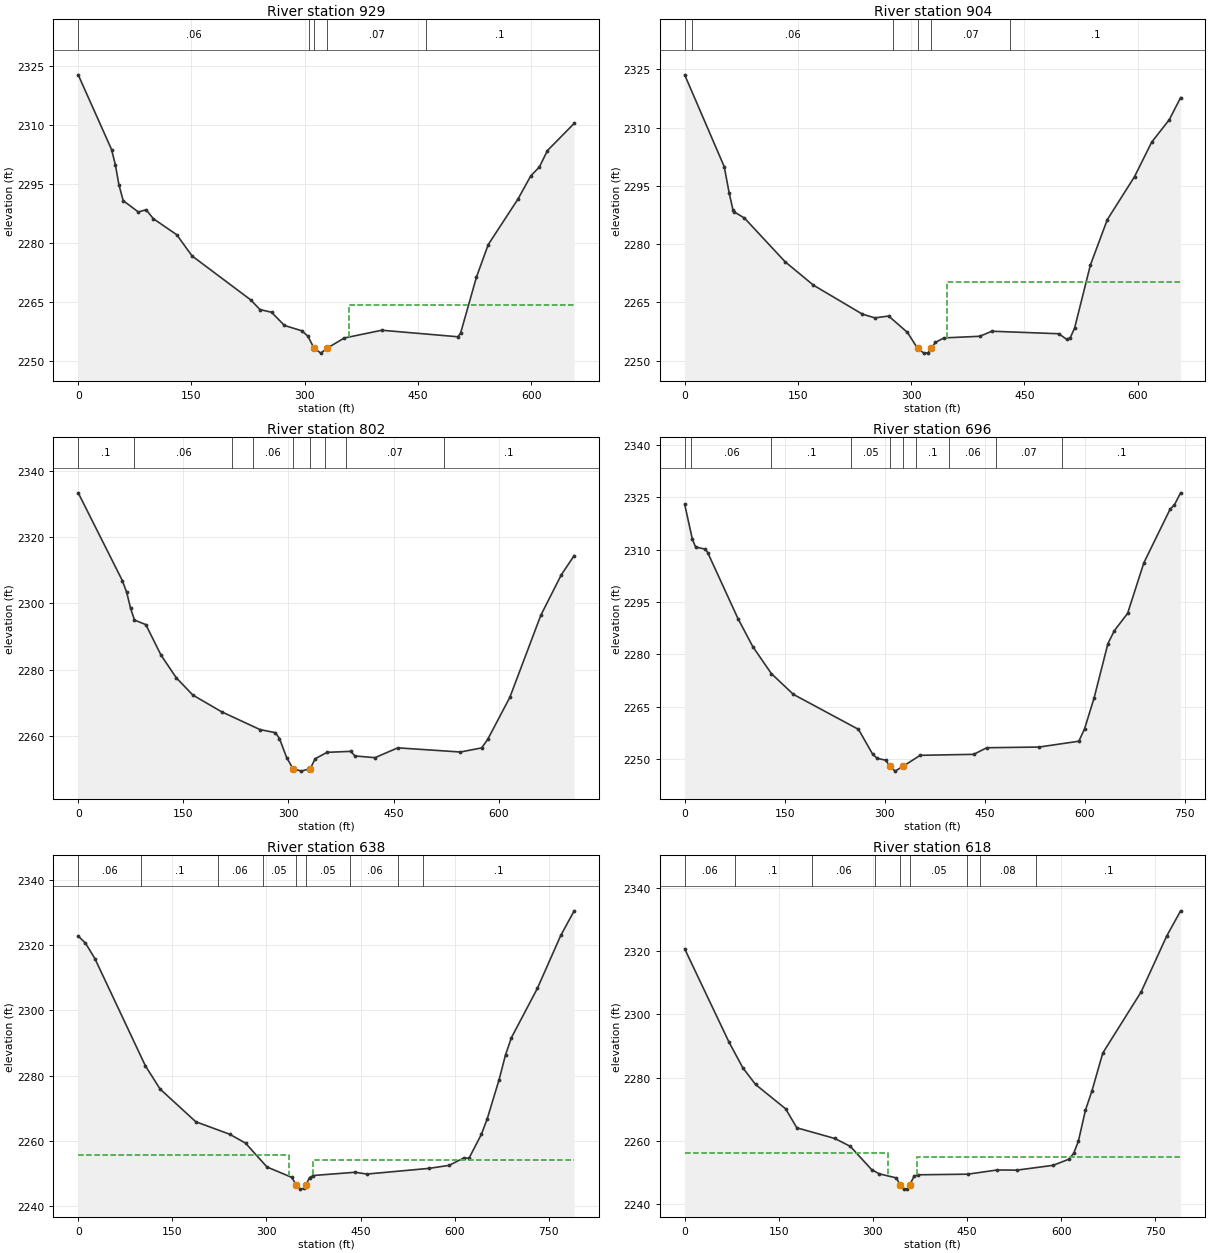
Type RM Length L Ch R = 1 ,929     ,25.8,25.8,25.8
XS GIS Cut Line= 4
2195527.30239233621852.0058321532195666.52942427621673.854596436
2195768.40965224621557.5055385392195946.08809342621346.052203013
#Sta/Elev= 30
       0 2322.82    44.2 2303.82    49.3 2299.86    53.9 2294.89    59.6 2290.83
    79.7 2287.95    89.9 2288.53    99.5 2286.25   130.5 2282.17   150.8 2276.78
   228.6 2265.59   240.7 2263.15   256.1 2262.46   273.1 2259.11   296.1 2257.75
   304.3 2256.36   312.1 2253.42   321.3 2252.07  330.19 2253.39   352.5 2255.92
   402.1 2257.89   502.9 2256.23   506.6 2257.23   527.5 2271.41   543.1 2279.66
   582.4 2291.21   599.4 2297.13   610.8 2299.37   621.5 2303.56   656.9 2310.47
#Mann= 5 ,-1,0
       0     .06       0   306.1     .07       0   312.1    .045       0
  330.19     .07       0  460.75      .1       0
#XS Ineff= 2 , 0
                          358.29         2264.35
Permanent Ineff=
       F       F
Bank Sta=312.1,330.19
XS Rating Curve= 0 ,0
Exp/Cntr(USF)=0,0
Exp/Cntr=0.3,0.1

Type RM Length L Ch R = 1 ,904     ,103.1,101.7,102
XS GIS Cut Line= 4
2195547.89323154621867.6045079472195687.12026348 621689.45327223
2195789.00049145621573.1042143332195966.67893263621361.650878807
#Sta/Elev= 30
       0 2323.57    52.4 2299.92    58.9 2293.19      64 2288.77    65.4  2288.3
    79.2 2286.69     133 2275.45   170.6 2269.41   235.5 2261.95     252    2261
   270.2 2261.47   295.1 2257.24   308.52253.152   316.9 2251.92   322.2 2251.99
  326.84 2253.14   331.9 2254.66   343.4 2255.84   391.1 2256.26   406.8 2257.56
   495.6 2256.91     506 2255.47   510.7 2255.87   516.5 2258.39   537.4  2274.6
   559.8 2286.29   595.9 2297.37   618.6 2306.25   641.9 2312.02   656.9 2317.72
#Mann= 6 ,-1,0
       0      .1       0      10     .06       0   276.1     .07       0
   308.5    .045       0  326.84     .07       0  430.75      .1       0
#XS Ineff= 2 , 0
                          348.09         2270.26
Permanent Ineff=
       F       F
Bank Sta=308.5,326.84
XS Rating Curve= 0 ,0
Exp/Cntr(USF)=0,0
Exp/Cntr=0.3,0.1

Type RM Length L Ch R = 1 ,802     ,107.3,106,104.3
XS GIS Cut Line= 4
2195560.98758005 621927.728764062195776.56526715621730.216246275
2195978.89516341621523.0689715252196042.72542831621414.677955668
#Sta/Elev= 30
       0 2333.34      63 2306.84    69.2 2303.28    74.8 2298.47    80.3 2294.95
    96.5 2293.56   118.2 2284.35   139.9 2277.53   163.6 2272.31   204.5 2267.28
   259.3  2261.9   281.5 2260.95   287.2 2259.18   297.5 2253.44  306.352250.133
   318.3 2249.35  331.222250.133   338.1 2253.08   355.1 2255.02   388.9 2255.32
   394.9 2253.93   423.5 2253.41     456 2256.38   545.4 2255.12   575.7 2256.36
   584.3 2258.91     616 2271.65   660.2 2296.41   689.4  2308.6707.7314  2314.4
#Mann= 9 ,-1,0
       0      .1       0      80     .06       0     220      .1       0
     250     .06       0  306.35    .045       0  331.22     .06       0
  352.38      .1       0  382.38     .07       0  522.38      .1       0
Bank Sta=306.35,331.22
XS Rating Curve= 0 ,0
Exp/Cntr(USF)=0,0
Exp/Cntr=0.3,0.1

Type RM Length L Ch R = 1 ,696     ,56.1,57.4,59.2
XS GIS Cut Line= 3
2195618.79612184621975.9025488862195845.21291052621816.929058961
2196116.19045017 621436.35615884
#Sta/Elev= 30
       0 2322.98    11.5 2313.03    16.3 2310.77      31 2310.14    34.5 2309.18
    79.9 2290.28   102.2 2282.22     130 2274.51     163 2268.56   260.7 2258.53
   281.8 2251.48   288.7 2250.22   301.5 2249.71   307.82247.962   315.6 2246.57
  327.612247.963   353.2  2251.1   433.5 2251.38   453.1 2253.27   531.7 2253.47
   591.2 2255.14   599.8  2258.7   614.2 2267.62   634.8  2283.1   644.6 2286.84
   664.3 2291.74   688.7 2306.24   728.1 2321.61   734.6 2322.86743.8414 2326.28
#Mann= 10 ,-1,0
       0      .1       0      10     .06       0     130      .1       0
     250     .05       0   307.8    .045       0  327.61     .05       0
  346.65      .1       0  396.65     .06       0  466.65     .07       0
  566.65      .1       0
Bank Sta=307.8,327.61
XS Rating Curve= 0 ,0
Exp/Cntr(USF)=0,0
Exp/Cntr=0.3,0.1

Type RM Length L Ch R = 1 ,638     ,21.2,20.8,21
XS GIS Cut Line= 5
2195632.26929192622024.8309981092195741.74421794 621970.63549018
2195842.54786269621886.0904978112195978.03663251  621758.1890991
2196160.13353915621459.029895333
#Sta/Elev= 30
       0 2322.74    11.6 2320.57    26.5 2315.86   107.1 2282.95   130.5 2275.85
   187.4 2265.83   241.3 2262.02   266.7 2259.28   300.8 2251.98   340.4 2248.79
  347.12 2246.54   354.1 2245.19   360.2 2245.41     363 2246.58   368.7 2248.75
   374.4 2249.36   441.2 2250.36     460 2249.81   559.6 2251.56   591.1 2252.48
   614.1 2254.71   622.8 2254.69   642.6 2262.03   651.9 2266.82   670.7 2278.74
     681 2286.39   690.3 2291.59   731.6 2306.68     769 2322.94   790.3 2330.47
#Mann= 9 ,-1,0
       0     .06       0     100      .1       0  222.16     .06       0
  293.72     .05       0  347.12    .045       0     363     .05       0
  433.72     .06       0  510.04     .08       0  550.04      .1       0
#XS Ineff= 2 , 0
           335.6 2255.53  374.87         2254.05
Permanent Ineff=
       F       F
Bank Sta=347.12,363
XS Rating Curve= 0 ,0
Exp/Cntr(USF)=0,0
Exp/Cntr=0.3,0.1

Type RM Length L Ch R = 1 ,618     ,77.2,75.5,73.3
XS GIS Cut Line= 5
2195653.01587451622033.4008424122195762.49080053621979.205334483
2195863.29444529621894.6603421142195998.78321511621766.758943403
2196180.88012175621467.599739636
#Sta/Elev= 30
       0 2320.68    70.5 2291.27    92.8 2283.06     113 2277.83   160.9 2270.15
   178.7 2264.15   239.2 2260.78   263.9  2258.3   297.8 2250.97   309.9 2249.62
   337.5 2248.31   343.42246.018   348.8 2244.78   354.9 2244.92   358.4 2246.01
   365.7 2248.92   372.4 2249.31   450.9  2249.5   498.1 2250.83   529.5 2250.78
   587.1  2252.3     612 2254.21   619.8 2256.05   627.4 2259.92   638.6  2269.7
   648.9 2275.75   666.3 2287.79   727.4 2307.09   768.2 2324.76   790.3 2332.69
#Mann= 9 ,-1,0
       0     .06       0      80      .1       0  202.16     .06       0
  303.72     .05       0   343.4    .045       0   358.4     .05       0
  450.04     .06       0  470.04     .08       0  560.04      .1       0
#XS Ineff= 2 , 0
           323.5 2256.09  370.13         2255.04
Permanent Ineff=
       F       F
Bank Sta=343.4,358.4
XS Rating Curve= 0 ,0
Exp/Cntr(USF)=0,0
Exp/Cntr=0.3,0.1

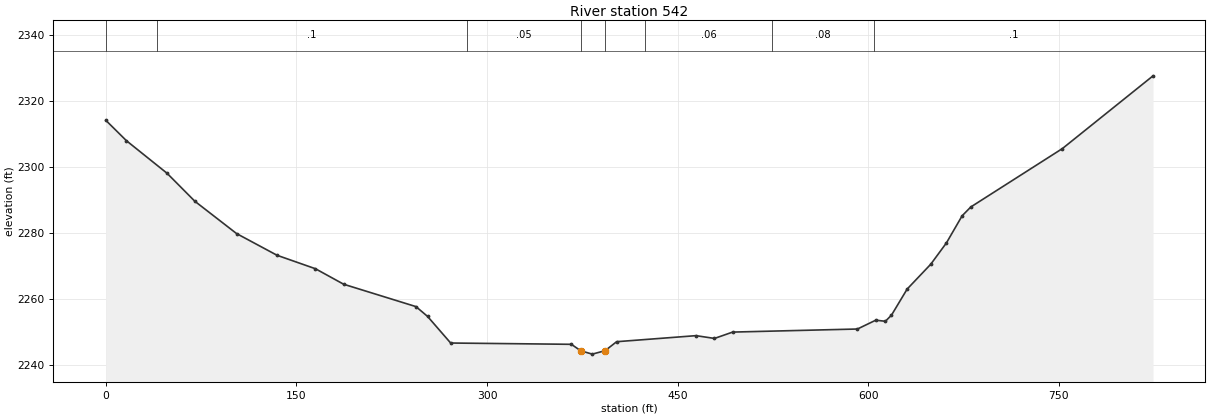
Type RM Length L Ch R = 1 ,542     ,71.8,72.2,72.6
XS GIS Cut Line= 3
2195689.85245446622098.7457001912195930.72137859621967.472136541
2196235.42056761621509.821180699
#Sta/Elev= 30
       0 2314.12    16.3 2307.92    48.2 2298.09    70.1 2289.61   102.9 2279.84
   134.8 2273.26     165 2269.19   187.2  2264.5   244.1 2257.73   253.2 2254.77
   271.4 2246.71   366.4 2246.32  373.72 2244.37   382.8 2243.35  392.89 2244.38
     402 2247.11   464.5 2248.94     479  2248.1   493.3 2250.02   591.5 2250.95
   605.9 2253.62   613.5 2253.29   618.3 2255.15   630.6 2263.03   649.2 2270.56
   661.5 2276.99   673.9 2285.22   680.7 2287.88   752.8 2305.56824.1238 2327.57
#Mann= 8 ,-1,0
       0     .06       0      40      .1       0  284.32     .05       0
  373.72    .045       0  392.89     .05       0  424.32     .06       0
  524.32     .08       0  604.32      .1       0
Bank Sta=373.72,392.89
XS Rating Curve= 0 ,0
Exp/Cntr(USF)=0,0
Exp/Cntr=0.3,0.1