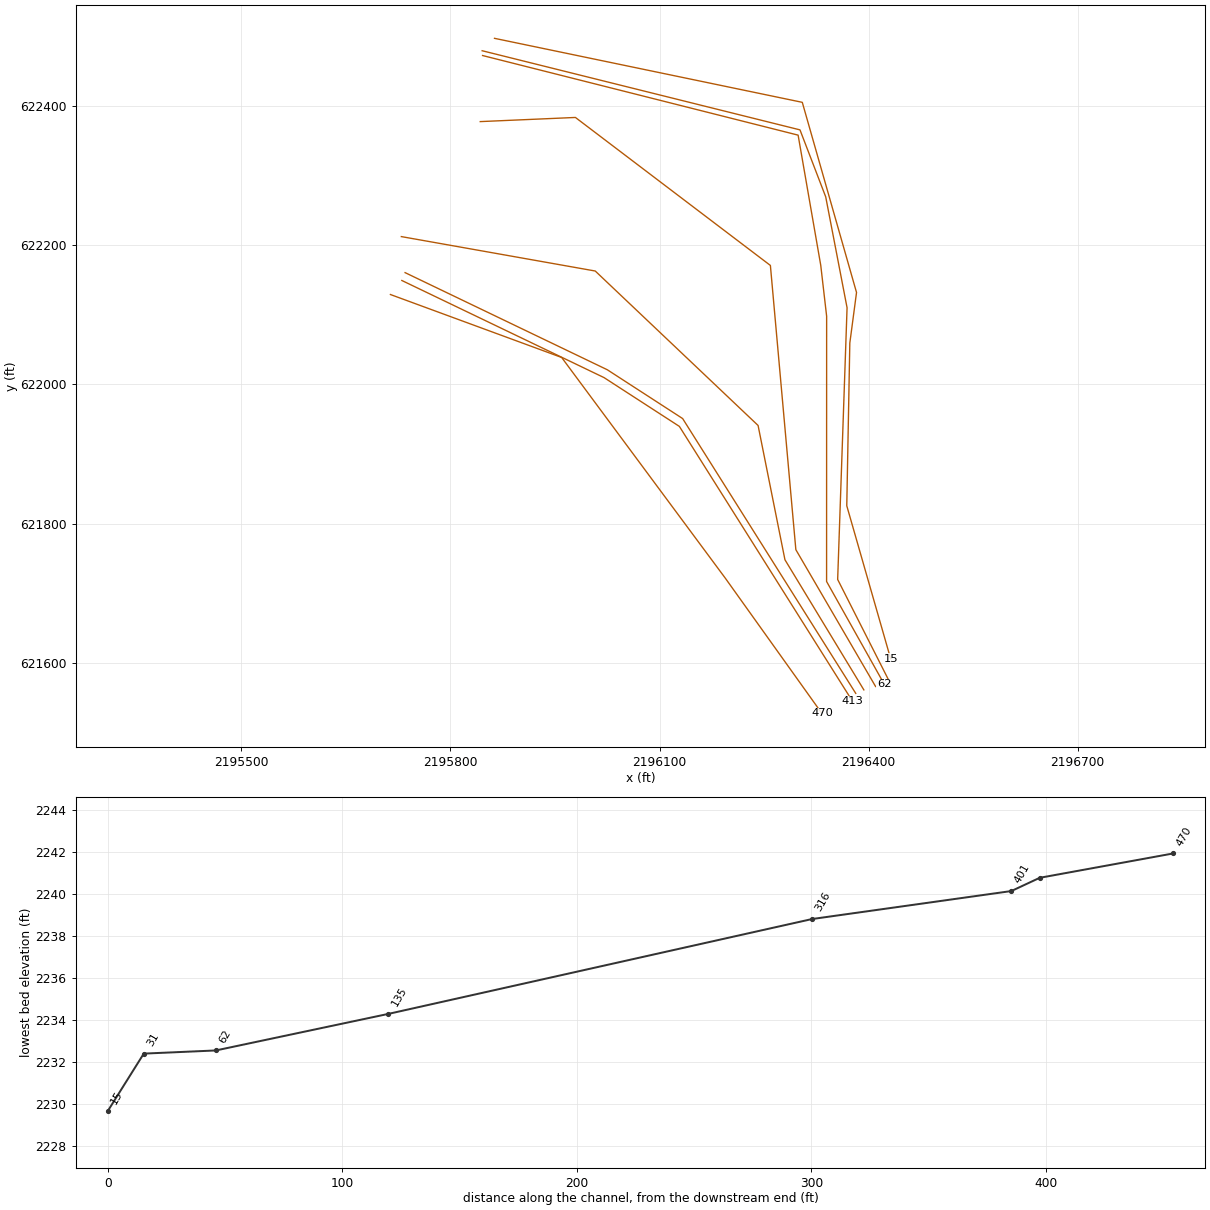
HEC-RAS study UPTROUTRN.prj: UPTROUTRN

--- UPTROUTRN.g01 (geometry) --- (continued)

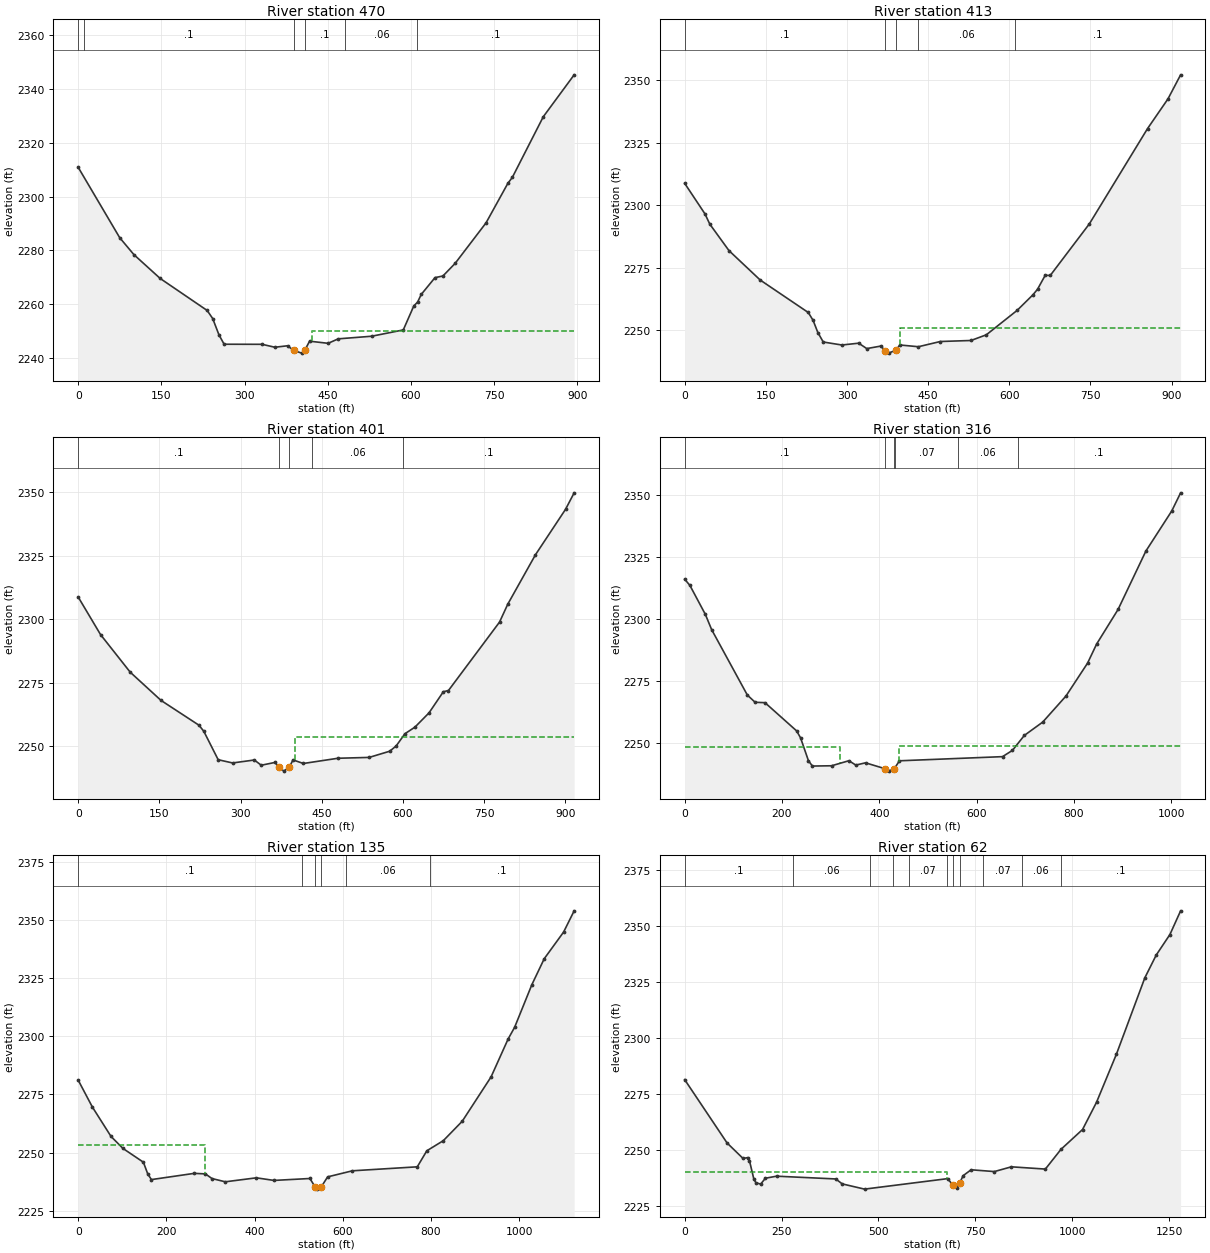
Type RM Length L Ch R = 1 ,470     ,53.4,57,60.6
XS GIS Cut Line= 4
2195713.93934687622128.8543157072195959.62564948622038.528469159
2196194.47285051621721.7858339312196332.97248188621527.886350008
#Sta/Elev= 30
       0 2310.82    74.8 2284.74   100.4 2278.46   147.9  2269.6   232.5 2257.75
   242.5 2254.76   253.8 2248.71   263.1 2245.22   331.7 2245.19   354.6  2244.1
   377.5 2244.65  388.352242.954   402.9 2241.92  408.562242.954   417.2 2246.35
   450.7 2245.56     469 2247.22     529 2248.18   586.2 2250.52   605.2 2259.42
     612 2260.84   618.6 2263.69   643.4 2269.92   657.7 2270.53   679.6 2275.18
   735.5 2290.25   774.8 2304.89   782.9 2307.11   838.7  2329.6894.3564 2345.14
#Mann= 6 ,-1,0
       0     .06       0      10      .1       0  388.35    .045       0
  408.56      .1       0  481.76     .06       0  611.76      .1       0
#XS Ineff= 2 , 0
                        421.3239            2250
Permanent Ineff=
       F       F
Bank Sta=388.35,408.56
XS Rating Curve= 0 ,0
Exp/Cntr(USF)=0,0
Exp/Cntr=0.3,0.1

Type RM Length L Ch R = 1 ,413     ,12.1,12.1,12.1
XS GIS Cut Line= 4
2195730.31143324622148.9878779172196020.47449343622009.616378204
2196128.50701283621939.6373507472196376.89454552621545.325853229
#Sta/Elev= 30
       0 2308.71    37.6 2296.45    46.4 2292.39    81.9 2281.78   139.6 2270.01
   228.4 2257.02   237.3  2253.9   246.1 2249.01   256.1 2245.21   290.5 2244.01
   321.6 2244.74   336.5 2242.58   362.5 2243.58   370.42241.798     377 2240.76
   389.92241.906   397.8 2244.02   431.9 2243.32   472.5 2245.41   529.2 2245.82
   557.5 2248.09   614.3 2257.84   643.6 2264.09   652.1 2266.31   666.3 2271.89
   675.7 2271.85     748 2292.51   855.5 2330.63   893.2 2342.49   916.6 2352.13
#Mann= 5 ,-1,0
       0      .1       0   370.4    .045       0   389.9      .1       0
   431.9     .06       0  610.62      .1       0
#XS Ineff= 2 , 0
                          397.83         2250.65
Permanent Ineff=
       F       F
Bank Sta=370.4,389.9
XS Rating Curve= 0 ,0
Exp/Cntr(USF)=0,0
Exp/Cntr=0.3,0.1

Type RM Length L Ch R = 1 ,401     ,87.3,84.9,83.5
XS GIS Cut Line= 4
2195734.98772552622160.2496636442196025.15078571 622020.87816393
2196133.18330511621950.899136474 2196381.5708378621556.587638956
#Sta/Elev= 30
       0 2308.68    41.3 2293.89    96.1  2279.1   153.1 2267.97   223.2 2258.21
   232.1 2255.83   258.7 2244.62   285.3 2243.35   325.5 2244.51   338.3 2242.45
   363.6 2243.55     3712241.732   380.2 2240.13   390.4 2241.82     397 2244.55
   416.1 2243.14   480.1  2245.2   537.7 2245.53   575.6 2247.96   587.5 2250.01
   603.9 2254.87   622.3 2257.45   648.4 2263.08   674.8 2271.39   684.3 2271.88
   778.7 2298.83   793.9 2305.87     845 2325.31   900.7 2343.24   916.6 2349.73
#Mann= 5 ,-1,0
       0      .1       0     371    .045       0   390.4      .1       0
   431.9     .06       0  600.62      .1       0
#XS Ineff= 2 , 0
                             400         2253.67
Permanent Ineff=
       F       F
Bank Sta=371,390.4
XS Rating Curve= 0 ,0
Exp/Cntr(USF)=0,0
Exp/Cntr=0.3,0.1

Type RM Length L Ch R = 1 ,316     ,187.2,180.6,174.1
XS GIS Cut Line= 5
2195729.59582694622211.9540945312196007.79943431622162.575965085
2196241.44229071621940.9765548872196279.98131857621748.281415585
2196393.18971291621561.607999386
#Sta/Elev= 30
       0 2316.22    10.7 2313.72    42.6 2301.98    55.4 2295.88   128.8 2269.48
   144.8 2266.57   165.1 2266.41   230.1 2255.03   238.2 2252.22   254.5 2242.94
   262.6 2240.85     302 2240.96   337.6    2243   351.7 2241.24   371.8 2242.15
   410.82239.837   419.6  2238.8  431.022239.838   441.5 2242.97   653.3 2244.64
   673.7 2247.17   698.2 2253.21   735.9 2258.57   783.8  2269.1   828.1 2282.35
   846.8 2290.07   890.8    2304     948 2327.56  1001.2 2343.741019.399 2351.05
#Mann= 6 ,-1,0
       0      .1       0   410.8    .045       0  431.02      .1       0
  432.55     .07       0  562.55     .06       0  684.57      .1       0
#XS Ineff= 2 , 0
          319.67 2248.41  440.15         2248.78
Permanent Ineff=
       F       F
Bank Sta=410.8,431.02
XS Rating Curve= 0 ,0
Exp/Cntr(USF)=0,0
Exp/Cntr=0.3,0.1

Type RM Length L Ch R = 1 ,135     ,73.6,73.6,73.9
XS GIS Cut Line= 5
2195842.80422128622376.9493075582195979.35215512622382.903710651
2196259.10071454622170.5763427992196295.63779864621762.733551032
 2196410.0505376621566.425377868
#Sta/Elev= 30
       0 2281.12    32.2 2269.55    74.4 2256.94   101.5 2251.78   147.8 2245.86
   157.8 2240.77     166 2238.39   263.3 2241.07   288.4 2240.84   303.4 2238.83
   333.6 2237.44     404 2239.15     444 2238.03   525.4 2238.86   536.7 2235.38
   541.5 2234.29   551.62235.403   565.6 2239.56   621.8 2242.17   768.9 2243.88
   790.5 2250.77   827.9 2255.12   870.8 2263.46   936.2 2282.53   974.9 2298.84
   989.6 2303.85  1028.8 2322.22  1056.8 2333.35  1100.7  2344.8  1124.6 2353.92
#Mann= 6 ,-1,0
       0      .1       0  507.88     .07       0   536.7    .045       0
   551.6     .07       0  607.88     .06       0  797.88      .1       0
#XS Ineff= 2 , 0
          287.37 2253.41
Permanent Ineff=
       F       F
Bank Sta=536.7,551.6
XS Rating Curve= 0 ,0
Exp/Cntr(USF)=0,0
Exp/Cntr=0.3,0.1

Type RM Length L Ch R = 1 ,62      ,30.2,30.7,31
XS GIS Cut Line= 6
2195846.15661365 622471.748578652196298.88285873622357.532759998
2196331.34049463622170.8578203482196339.80159437622097.673412492
2196339.73211568621717.1083482712196422.45981608621569.774531239
#Sta/Elev= 30
       0 2281.44   109.3 2253.18   150.6 2246.24     163 2246.63   167.1  2245.3
   178.4 2237.09   183.6 2235.43     196 2234.79   208.3 2237.42   237.2 2238.33
   389.9 2237.09   406.4 2234.89   464.1 2232.55   678.3 2237.23   692.62234.278
   702.4 2233.11   709.22235.193   718.5 2238.56     739 2241.19     799 2240.39
     843 2242.51   930.6  2241.5     971 2250.33  1026.6 2259.17  1062.6 2271.32
  1113.9 2292.77  1187.3  2326.9  1216.7 2337.07    1252 2346.22  1279.6  2356.8
#Mann= 11 ,-1,0
       0      .1       0     280     .06       0  476.91      .1       0
  536.91     .06       0  577.73     .07       0  676.43     .06       0
   692.6    .045       0   709.2     .06       0  770.11     .07       0
  870.11     .06       0  970.11      .1       0
#XS Ineff= 2 , 0
        677.9602    2240
Permanent Ineff=
       F       F
Bank Sta=692.6,709.2
XS Rating Curve= 0 ,0
Exp/Cntr(USF)=0,0
Exp/Cntr=0.3,0.1

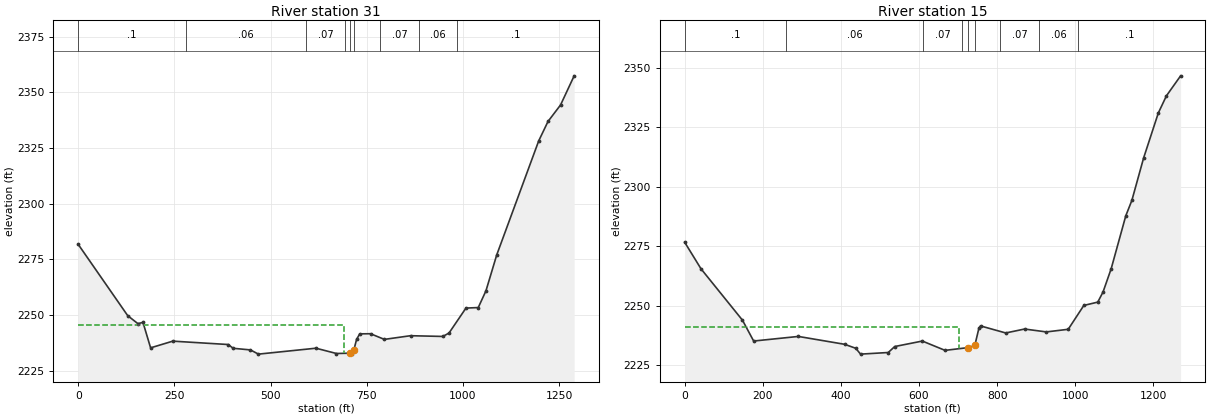
Type RM Length L Ch R = 1 ,31      ,14.8,15.4,15.7
XS GIS Cut Line= 6
2195845.54003873622478.6333001492196301.56760873 622365.07774648
2196338.46862005622269.011829598 2196369.1166515622109.890780021
2196355.62216535621720.0314798692196429.76642096621573.688060312
#Sta/Elev= 30
       0 2281.69   128.8 2249.65   155.2 2246.09   168.4 2246.65   188.2 2235.22
   245.9 2238.23   390.2 2236.71   402.7 2235.02   447.9 2234.29   468.5  2232.4
   618.1 2235.06   671.4 2232.68705.37712232.815   711.7 2232.57716.48662234.195
   723.8 2239.02   731.9  2241.5     760 2241.56     796 2239.02     864 2240.67
   948.1 2240.34   964.1 2241.88  1008.1 2253.08  1040.1 2253.31  1060.1 2260.83
  1088.1 2276.95  1197.3 2328.18  1221.4 2336.87  1254.1  2344.3  1289.4 2357.37
#Mann= 9 ,-1,0
       0      .1       0     280     .06       0  592.86     .07       0
  693.76     .06       0705.3771    .045       0716.4866     .06       0
  785.23     .07       0  885.23     .06       0  985.23      .1       0
#XS Ineff= 2 , 0
          690.82 2245.45
Permanent Ineff=
       F       F
Bank Sta=705.3771,716.4866
XS Rating Curve= 0 ,0
Exp/Cntr(USF)=0,0
Exp/Cntr=0.3,0.1

Type RM Length L Ch R = 1 ,15      ,,,
XS GIS Cut Line= 6
2195863.27158643622496.4213854592196304.86238816622404.605476187
2196382.68730174622131.781060066 2196373.0684922 622059.20276988
2196368.69630604621825.7280291612196431.65578668 621606.24428414
#Sta/Elev= 30
       0 2276.66    41.8  2265.5     148 2243.91   176.6 2235.16     291 2237.09
   409.5 2233.79   438.1 2232.11   450.3 2229.66   521.2 2230.34   537.8 2232.85
   608.5 2235.15   666.7 2231.24   724.7 2232.38   742.9 2233.34   753.5 2240.65
   757.5 2241.51     822 2238.55   870.3  2240.2     926 2238.99     982 2240.09
    1022 2250.12  1057.7 2251.51  1071.2 2255.78    1092 2265.53  1129.4 2287.76
    1145 2294.25  1175.2 2312.14  1212.7 2330.96  1233.5 2338.18  1269.8 2346.57
#Mann= 9 ,-1,0
       0      .1       0     260     .06       0  611.04     .07       0
  711.04     .06       0   724.7    .045       0   742.9     .06       0
  807.96     .07       0  907.96     .06       0 1007.96      .1       0
#XS Ineff= 2 , 0
          703.38 2240.91
Permanent Ineff=
       F       F
Bank Sta=724.7,742.9
XS Rating Curve= 0 ,0
Exp/Cntr(USF)=0,0
Exp/Cntr=0.3,0.1
LCMann Table=0

Chan Stop Cuts=-1
Use User Specified Reach Order=0
Composite Channel Slope=5